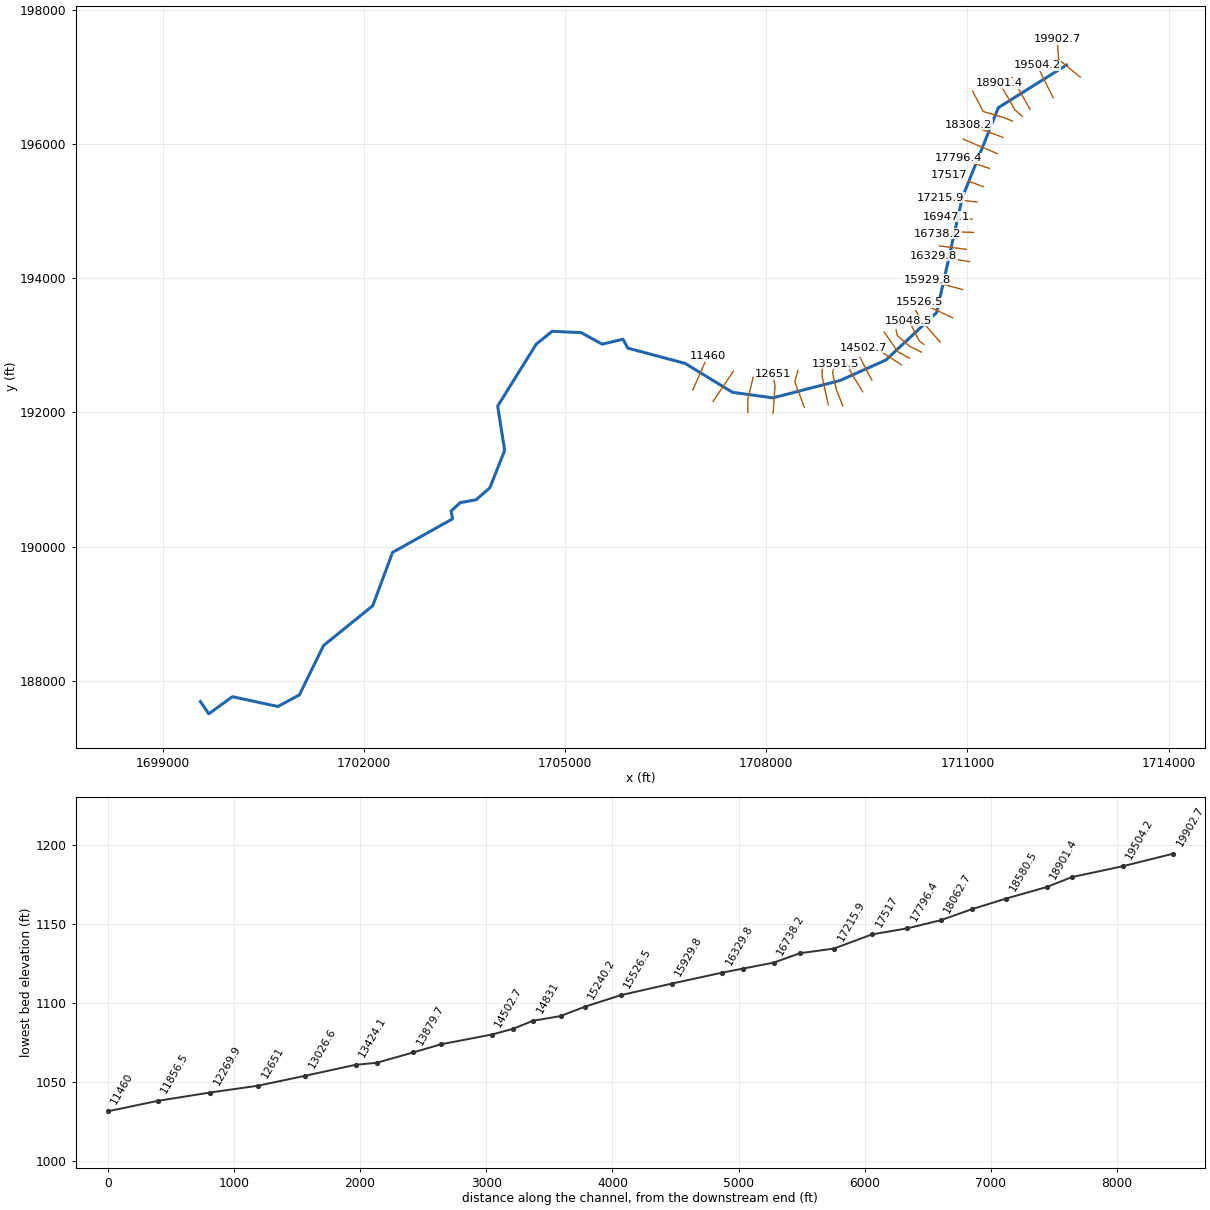
--- smsfrk.prj (project) ---

Proj Title=smsfrk
Current Plan=p01
Default Exp/Contr=0,0
English Units
Geom File=g01
Flow File=f01
Plan File=p01
BEGIN DESCRIPTION:
END DESCRIPTION:
DSS File=dss
DSS Export Rating Curves= 0
DSS Export Rating Curve Sorted= 0
DSS Export Volume Flow Curves= 0
DXF OffsetX= 0
DXF OffsetY= 0
DXF ScaleX= 0
DXF ScaleY= 0

--- smsfrk.p01 (plan) ---

Plan Title=Approximate Study - 100yr
Program Version=4.00
Short Identifier=Approximate
Geom File=g01
Flow File=f01
Subcritical Flow
K Sum by GR= 0
Std Step Tol= 0.01
Critical Tol= 0.01
Num of Std Step Trials= 20
Max Error Tol= 0.3
Flow Tol Ratio= 0.001
Split Flow NTrial= 30
Split Flow Tol= 0.02
Split Flow Ratio= 0.02
Log Output Level= 0
Friction Slope Method= 1
Unsteady Friction Slope Method= 2
Unsteady Bridges Friction Slope Method= 1
Parabolic Critical Depth
Global Vel Dist= 0 , 0 , 0
Global Log Level= 0
CheckData=True
Encroach Param=-1 ,0,0, 0
Run HTab= 0
Run UNet= 0
Run PostProcess= 0
Run WQNet= 0
UNET Theta= 0
UNET Theta Warmup= 0
UNET ZTol= 0
UNET ZSATol= 0
UNET MxIter= 0
UNET MaxInSteps= 0
UNET DtIC= 0
UNET DtMin= 0
UNET MaxCRTS= 0
UNET WFStab= 0
UNET SFStab= 0
UNET WFX= 1
UNET SFX= 1
UNET DSS MLevel= 1
UNET DZMax Abort= 0
UNET Convert EG Bridges= 0
UNET Use Existing IB Tables= 0
UNET Froude Reduction=False
UNET Froude Limit= 0
UNET Froude Power= 0
UNET Time Slicing=0,0, 5
DSS File=dss
Write IC File= 0
Echo Input=False
Echo Output=False
Write Detailed= 0
Detailed Automatic Start=False, 0
WQ ULTIMATE=-1
WQ Max Comp Step=1HOUR
WQ Output Interval=15MIN
WQ Output Selected Increments= 0
WQ Output face flow=0
WQ Output face velocity=0
WQ Output face area=0
WQ Output face dispersion=0
WQ Output cell volume=0
WQ Output cell surface area=0
WQ Output cell continuity=0
WQ Output face conc=0
WQ Output face dconc_dx=0
WQ Output face courant=0
WQ Output face peclet=0
WQ Output face adv mass=0
WQ Output face disp mass=0
WQ Output cell mass=0
WQ Output cell source sink temp=0
WQ Output cell source sink nsm=0
WQ Output MaxMinRange=-1
WQ Daily Max Min Mean=-1
WQ Daily Range=0
WQ Daily Time=0
WQ Create Restart=0
WQ Fixed Restart=0
WQ System Summary=False
Sorting and Armoring Iterations= 10
XS Update Threshold= 0.02
Hydraulics Update Threshold= 0.02
Energy Slope Method= 1
Volume Change Method= 0
XS Weighting Method= 0
Number of US Weighted Cross Sections= 1
Number of DS Weighted Cross Sections= 1
Upstream XS Weight=0.25
Main XS Weight=0.5
Downstream XS Weight=0.25
Number of DS XS's Weighted with US Boundary= 1
Upstream Boundary Weight= 1
Weight of XSs Associated with US Boundary= 0
Number of US XS's Weighted with DS Boundary= 1
Downstream Boundary Weight= 0.5
Weight of XSs Associated with DS Boundary= 0.5
Sediment Output Level= 4
Mass or Volume Output= 0
Output Increment Type= 1
Profile and TS Output Increment= 10
XS Output Flag= 0
XS Output Increment= 10
Disregard all LS=0
Disregard all Conn=0
Disregard all Breaches=0
Disregard all Pumps=0

--- smsfrk.f01 (steady flow) ---

Flow Title=USGS Regression Equation
Program Version=4.00
Number of Profiles= 1
Profile Names=P100yr
River Rch & RM=smsfrk,Main            ,19902.7
     430
River Rch & RM=smsfrk,Main            ,19103.5
     440
River Rch & RM=smsfrk,Main            ,18308.2
     486
River Rch & RM=smsfrk,Main            ,17517
     519
River Rch & RM=smsfrk,Main            ,15526.5
     563
River Rch & RM=smsfrk,Main            ,15240.2
     732
River Rch & RM=smsfrk,Main            ,13591.5
     800
River Rch & RM=smsfrk,Main            ,10714.6
     866
River Rch & RM=smsfrk,Main            ,10433.5
    1052
River Rch & RM=smsfrk,Main            ,9482.8
    1063
River Rch & RM=smsfrk,Main            ,6018.7
    1178
River Rch & RM=smsfrk,Main            ,255.7
    1308
Boundary for River Rch & Prof#=smsfrk,Main            , 1
Up Type= 0
Dn Type= 3
Dn Slope=0.018
DSS Import GetInterval= 0
DSS Import GetPeak= 0
DSS Import FillOption= 0

--- smsfrk.g01 (geometry) ---

Geom Title=USGS 3m DEM
Program Version=4.00

River Reach=smsfrk          ,Main
Reach XY= 30
     1712479.344      197175.535     1711462.417      196540.118
     1710925.754      195205.542     1710541.406      193486.712
     1709782.373      192779.212     1709102.717      192476.211
     1708098.972      192216.647     1707496.271      192299.233
      1706789.24      192730.223     1705934.599      192957.429
     1705863.459      193089.598     1705550.958      193016.681
     1705239.761      193188.556     1704806.167      193208.087
     1704569.187      193016.681     1703993.667      192094.806
     1704097.833      191433.348        1703877.      190877.659
     1703671.456       190698.58     1703433.771      190656.004
     1703298.354      190529.702     1703321.792      190415.119
     1702426.083      189914.854     1702130.386      189120.848
     1701396.503      188527.766     1701035.774      187792.352
     1700715.842      187619.502     1700036.636      187765.379
      1699684.87      187510.625     1699560.073      187692.462

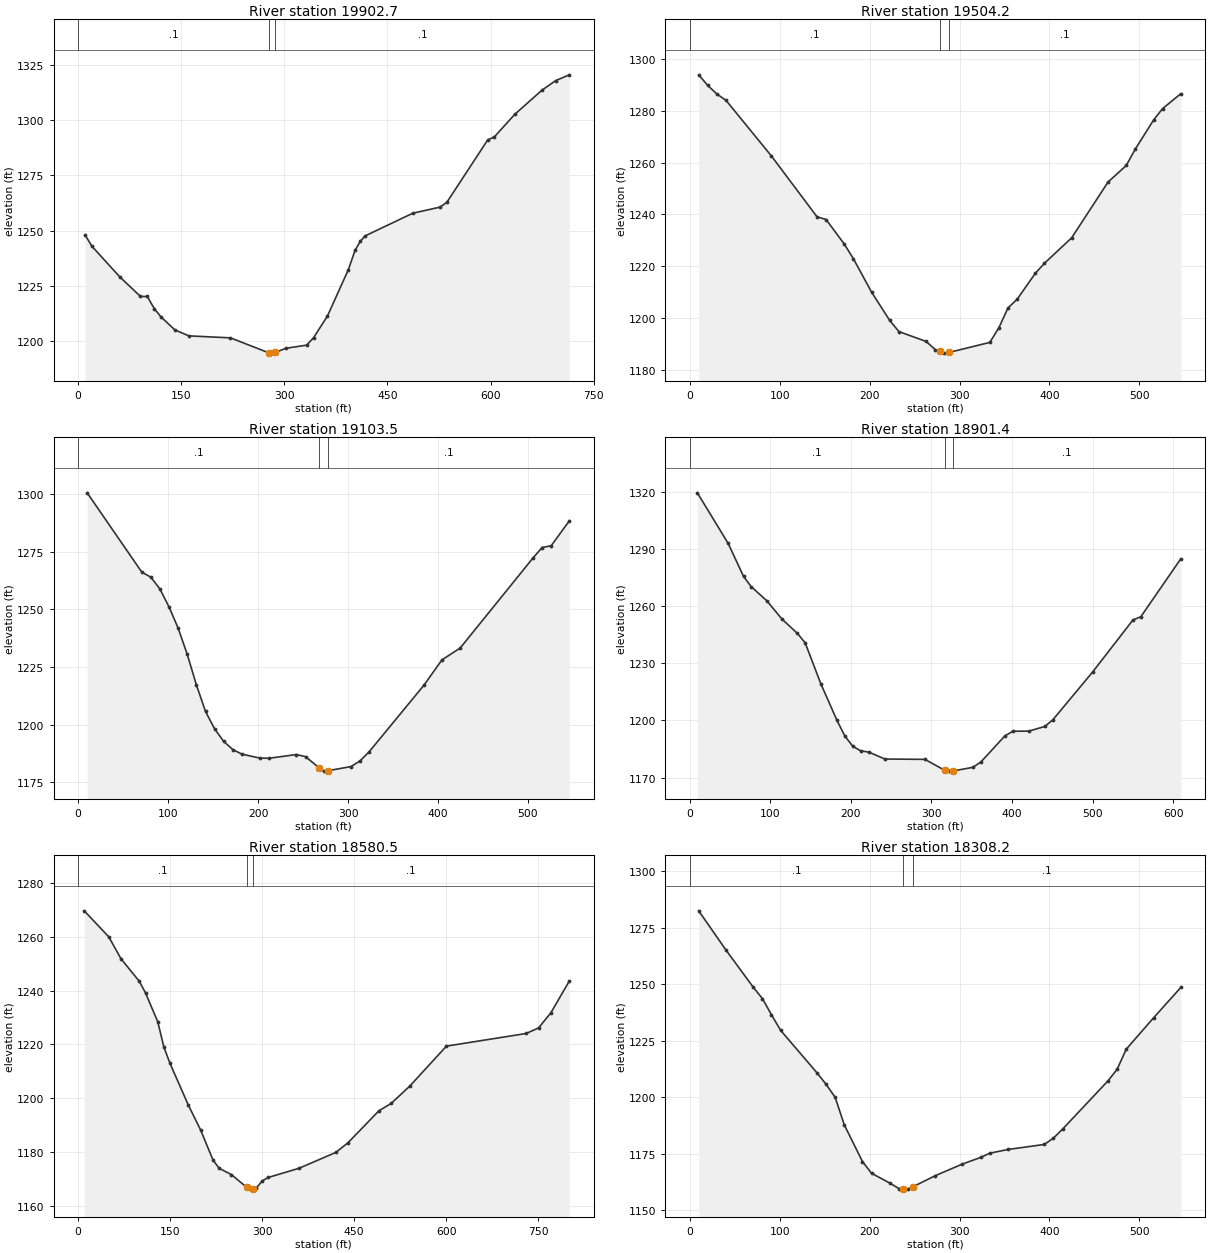
Type RM Length L Ch R = 1 ,19902.7 ,407,398.5,390.1
XS GIS Cut Line= 4
     1712683.724      196994.268     1712371.638      197249.154
     1712360.462      197258.575     1712339.848      197554.862
#Sta/Elev= 30
    10.1 1248.09    20.1 1242.93    60.4 1229.13    90.7 1220.18   100.7 1220.17
   110.8 1214.66   120.9  1210.8     141 1204.97   161.2 1202.32   221.6 1201.42
   277.1 1194.68   282.1  1194.5   287.1 1194.85   302.2 1196.68   332.4 1198.12
   342.5 1201.47   362.7  1211.3   392.9 1232.15   402.9 1241.06   410.3  1245.1
   417.6 1247.64   486.9 1257.91   526.5 1260.66   536.4 1262.84   595.8 1291.09
   605.7 1292.55   635.4 1302.78     675 1313.72   694.8 1318.01   714.6 1320.62
#Mann= 3 , 0 , 0
       0      .1       0   277.1    .045       0   287.1      .1       0
Bank Sta=277.1,287.1
XS Rating Curve= 0 ,0
Exp/Cntr=0.3,0.1

Type RM Length L Ch R = 1 ,19504.2 ,399.7,400.7,401.6
XS GIS Cut Line= 3
     1712281.055      196684.579     1712158.967      196928.758
     1712036.878      197172.937
#Sta/Elev= 30
    10.1 1293.82    20.2 1289.72    30.3 1286.42    40.4 1284.01      91 1262.51
   141.6 1239.11   151.7 1238.07   171.9 1228.62     182 1222.98   202.2 1210.11
   222.4 1199.18   232.6 1194.88   262.9 1191.08     273 1187.93   278.1 1187.24
   283.1 1186.58   288.2 1186.83   333.7 1190.72   343.8 1196.41   353.9 1204.02
     364 1207.32   384.2 1217.32   394.3 1221.17   424.7 1231.04   465.1 1252.51
   485.3 1258.89   495.4 1265.22   515.7 1276.41   525.8 1280.84     546 1286.56
#Mann= 3 , 0 , 0
       0      .1       0   278.1    .045       0   288.2      .1       0
Bank Sta=278.1,288.2
XS Rating Curve= 0 ,0
Exp/Cntr=0.3,0.1

Type RM Length L Ch R = 1 ,19103.5 ,202.1,202.2,202.2
XS GIS Cut Line= 3
     1711934.361      196514.415      1711800.52      196752.356
     1711666.679      196990.296
#Sta/Elev= 30
    10.1  1300.7    70.8 1266.23    80.9 1264.04      91 1258.86   101.1 1251.07
   111.2 1241.89   121.3  1230.5   131.4 1217.33   141.6  1205.7   151.7 1198.15
   161.8  1192.7   171.9 1189.13     182 1187.15   202.2 1185.41   212.3 1185.35
   242.7 1186.97   252.8 1186.05   267.9 1181.19     273 1179.76   278.1 1179.97
   303.3 1181.74   313.4 1184.22   323.6 1188.22   384.2 1217.01   404.4  1228.1
   424.7 1233.27   505.6 1272.39   515.7 1276.93   525.8  1277.7     546 1288.54
#Mann= 3 , 0 , 0
       0      .1       0   267.9    .045       0   278.1      .1       0
Bank Sta=267.9,278.1
XS Rating Curve= 0 ,0
Exp/Cntr=0.3,0.1

Type RM Length L Ch R = 1 ,18901.4 ,305.3,320.9,336.4
XS GIS Cut Line= 3
     1711823.153      196406.342     1711708.095      196507.031
     1711482.879      196904.023
#Sta/Elev= 30
     9.6 1319.55    47.8 1293.01    66.9 1275.66    76.4 1270.27    95.6 1262.93
   114.7 1253.19   133.8  1245.7   143.3 1240.79   162.8 1219.24   182.7 1200.14
   192.6 1191.79   202.5 1186.42   212.4 1184.04   222.4 1183.39   242.2 1179.76
   291.8 1179.59   316.4 1173.86   321.6 1173.41   326.7 1173.48   351.3  1175.4
   361.3 1178.21     391  1191.9     401 1194.35   420.8 1194.43   440.6 1196.87
   450.6  1200.4   500.2 1225.63   549.8 1252.75   559.7 1254.51   609.3 1284.94
#Mann= 3 , 0 , 0
       0      .1       0   316.4    .045       0   326.7      .1       0
Bank Sta=316.4,326.7
XS Rating Curve= 0 ,0
Exp/Cntr=0.3,0.1

Type RM Length L Ch R = 1 ,18580.5 ,273.6,272.3,270.9
XS GIS Cut Line= 4
      1711673.74      196339.072     1711534.411      196394.422
     1711236.667      196482.219     1711078.252       196783.78
#Sta/Elev= 30
      10 1269.75      50 1260.07      70 1251.88    99.9 1243.48   109.9 1239.18
   129.9 1228.44   139.9 1219.02   149.9 1212.92     180  1197.3     200 1188.05
     220 1176.95     230 1173.88   250.1 1171.54   274.9 1166.81   280.1 1166.14
   285.3 1166.27   290.1 1166.38   300.1  1169.2   310.1 1170.49   360.2  1173.9
   420.3 1179.81   440.3 1183.45   490.4 1195.29   510.4 1198.04   540.5 1204.42
   600.6 1219.38   730.8 1224.09   750.9 1226.18   770.9 1231.79     801 1243.64
#Mann= 3 , 0 , 0
       0      .1       0   274.9    .045       0   285.3      .1       0
Bank Sta=274.9,285.3
XS Rating Curve= 0 ,0
Exp/Cntr=0.3,0.1

Type RM Length L Ch R = 1 ,18308.2 ,246.4,245.5,244.5
XS GIS Cut Line= 3
     1711531.601       196096.77     1711275.288      196190.751
     1711018.975      196284.733
#Sta/Elev= 30
    10.1 1282.49    40.4 1265.15    70.8 1248.65    80.9 1243.68      91 1236.51
   101.1 1229.65   141.6 1210.81   151.7 1205.73   161.8 1199.96   171.9 1187.81
   192.1 1171.59   202.2 1166.38   222.4 1162.08   232.6 1159.62   237.5  1159.5
   242.7 1159.37   247.9 1160.36     273 1165.31   303.3 1170.48   323.6 1173.41
   333.7 1175.27   353.9 1176.91   394.3 1179.14   404.4 1181.94   414.6 1185.93
   465.1 1207.31   475.2 1212.41   485.3 1221.29   515.7 1235.17     546  1248.6
#Mann= 3 , 0 , 0
       0      .1       0   237.5    .045       0   247.9      .1       0
Bank Sta=237.5,247.9
XS Rating Curve= 0 ,0
Exp/Cntr=0.3,0.1

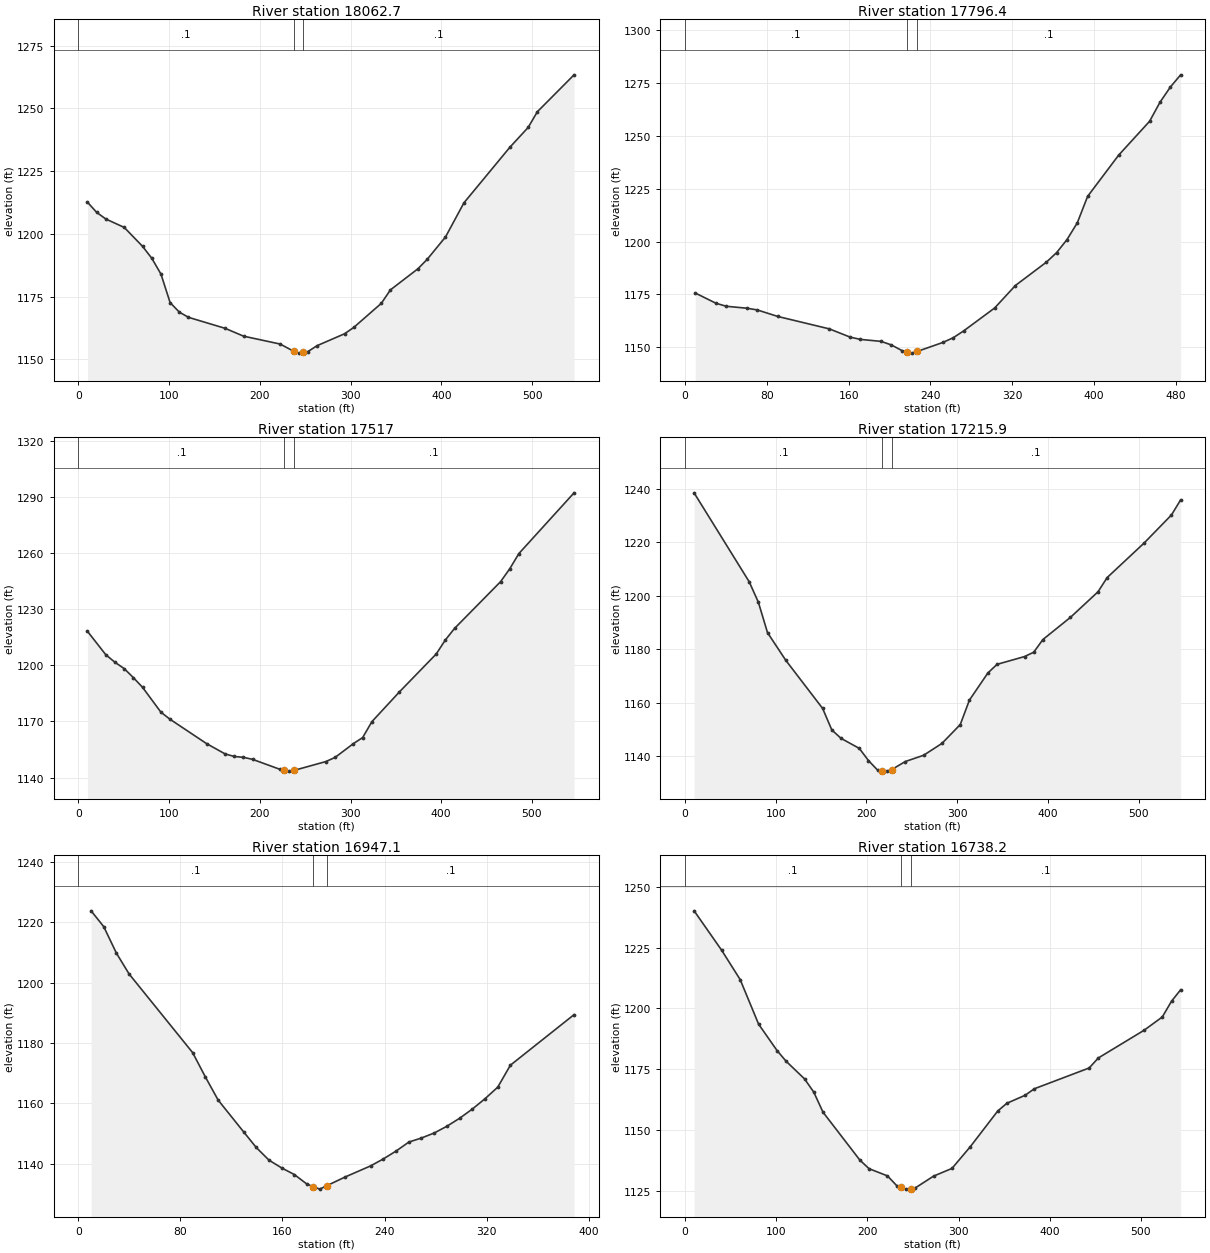
Type RM Length L Ch R = 1 ,18062.7 ,264.6,266.3,268
XS GIS Cut Line= 3
      1711442.59      195855.836     1711191.308      195962.545
     1710940.027      196069.253
#Sta/Elev= 30
    10.1 1212.59    20.2 1208.53    30.3 1205.89    50.6 1202.53    70.8 1194.97
    80.9 1190.24      91 1183.95   101.1 1172.57   111.2 1168.79   121.3  1166.7
   161.8  1162.3     182 1159.19   222.4 1156.04   237.4 1153.12   242.7 1152.43
   247.9 1152.73   252.8 1153.02   262.9 1155.39   293.2 1160.14   303.3 1162.65
   333.7 1172.27   343.8 1177.66   374.1 1186.07   384.2  1189.8   404.4 1198.72
   424.7 1212.33   475.2 1234.44   495.4 1242.37   505.6 1248.65     546 1263.36
#Mann= 3 , 0 , 0
       0      .1       0   237.4    .045       0   247.9      .1       0
Bank Sta=237.4,247.9
XS Rating Curve= 0 ,0
Exp/Cntr=0.3,0.1

Type RM Length L Ch R = 1 ,17796.4 ,280.1,279.4,278.7
XS GIS Cut Line= 2
      1711328.26      195635.736     1710867.647      195785.881
#Sta/Elev= 30
    10.1  1175.7    30.3 1170.87    40.4 1169.43    60.6 1168.51    70.7  1167.7
    90.8 1164.61   141.3 1158.72   161.5 1154.84   171.6 1153.76   191.8 1152.82
   201.9 1151.12     212 1148.51   216.8 1147.92     222 1147.27   227.3 1148.11
   252.3 1152.35   262.4 1154.59   272.5  1157.8   302.8 1168.64     323 1179.25
   353.3 1190.29   363.3  1194.8   373.4 1200.93   383.5 1208.88   393.6  1221.4
   423.9 1240.88   454.2 1256.93   464.3  1265.9   474.4 1273.06   484.5 1278.88
#Mann= 3 , 0 , 0
       0      .1       0   216.8    .045       0   227.3      .1       0
Bank Sta=216.8,227.3
XS Rating Curve= 0 ,0
Exp/Cntr=0.3,0.1

Type RM Length L Ch R = 1 ,17517   ,296.4,301.1,305.8
XS GIS Cut Line= 3
     1711238.752      195362.505     1710982.575      195456.612
     1710721.152      195536.929
#Sta/Elev= 30
    10.1 1218.12    30.3 1205.61    40.4 1201.58    50.5 1198.23    60.6 1193.43
    70.8  1188.2      91 1174.95   101.1 1171.14   141.5  1158.1   161.7 1152.66
   171.8 1151.26   181.9 1150.82   192.1 1149.73   222.4 1144.37   227.2 1143.93
   232.5 1143.44   237.8 1143.84   272.9 1148.56     283 1150.76   303.3 1158.18
   313.4 1161.37   323.6 1169.88   353.9 1185.76   394.5 1206.03   404.6 1213.54
   414.7 1219.69   465.4 1244.65   475.5 1251.52   485.6 1259.68   546.4 1292.12
#Mann= 3 , 0 , 0
       0      .1       0   227.2    .045       0   237.8      .1       0
Bank Sta=227.2,237.8
XS Rating Curve= 0 ,0
Exp/Cntr=0.3,0.1

Type RM Length L Ch R = 1 ,17215.9 ,268.3,268.8,269.3
XS GIS Cut Line= 3
     1711144.392      195133.711     1710873.318      195166.078
     1710602.243      195198.446
#Sta/Elev= 30
    10.1 1238.42    70.8 1205.21    80.9 1197.57      91 1186.19   111.2 1175.83
   151.7 1157.89   161.8 1149.87   171.9 1146.74   192.1 1142.97   202.2 1138.42
   212.3 1134.84   217.1 1134.67   222.4 1134.48   227.8 1135.06   242.7 1138.06
   262.9  1140.4   283.1 1144.83   303.3 1151.88   313.4 1161.02   333.7 1171.14
   343.8 1174.36   374.1 1177.27   384.2 1178.89   394.3 1183.63   424.7 1191.93
     455 1201.45   465.1 1206.78   505.6 1219.61   535.9 1230.15     546 1235.79
#Mann= 3 , 0 , 0
       0      .1       0   217.1    .045       0   227.8      .1       0
Bank Sta=217.1,227.8
XS Rating Curve= 0 ,0
Exp/Cntr=0.3,0.1

Type RM Length L Ch R = 1 ,16947.1 ,207.5,208.9,210.2
XS GIS Cut Line= 2
     1711068.688      194877.379     1710681.875      194913.006
#Sta/Elev= 30
      10 1223.77    19.9 1218.54    29.9  1209.7    39.8 1202.84    89.6 1176.77
    99.6 1168.69   109.6 1161.04   129.5 1150.54   139.4 1145.36   149.4 1141.15
   159.4 1138.56   169.3 1136.37   179.3 1133.16   183.9 1132.41   189.2 1131.54
   194.6 1132.65   209.2 1135.58   229.1 1139.25     239 1141.54     249 1144.15
     259 1147.13   268.9 1148.48   278.9 1150.14   288.8 1152.37   298.8 1155.02
   308.8 1158.08   318.7 1161.49   328.7 1165.33   338.6 1172.61   388.5 1189.36
#Mann= 3 , 0 , 0
       0      .1       0   183.9    .045       0   194.6      .1       0
Bank Sta=183.9,194.6
XS Rating Curve= 0 ,0
Exp/Cntr=0.3,0.1

Type RM Length L Ch R = 1 ,16738.2 ,243.4,241.4,239.4
XS GIS Cut Line= 3
     1711093.043       194681.93     1710790.289      194689.982
     1710551.104      194663.545
#Sta/Elev= 30
    10.1 1240.19    40.4  1223.9    60.6 1211.87    80.8 1193.52     101 1182.66
     111 1178.23   131.2 1170.97   141.3 1165.52   151.4 1157.28   191.8 1137.55
   201.9    1134   222.1 1131.03   232.2 1127.03   236.9 1126.35   242.3 1125.58
   247.7 1125.82   252.4 1126.03   272.6 1130.93   292.8 1134.11   312.9 1143.05
     343 1157.77     353 1160.94     373 1164.23   383.1 1166.91   443.2 1175.47
   453.3  1179.6   503.4    1191   523.4 1196.47   533.5 1202.96   543.5 1207.68
#Mann= 3 , 0 , 0
       0      .1       0   236.9    .045       0   247.7      .1       0
Bank Sta=236.9,247.7
XS Rating Curve= 0 ,0
Exp/Cntr=0.3,0.1

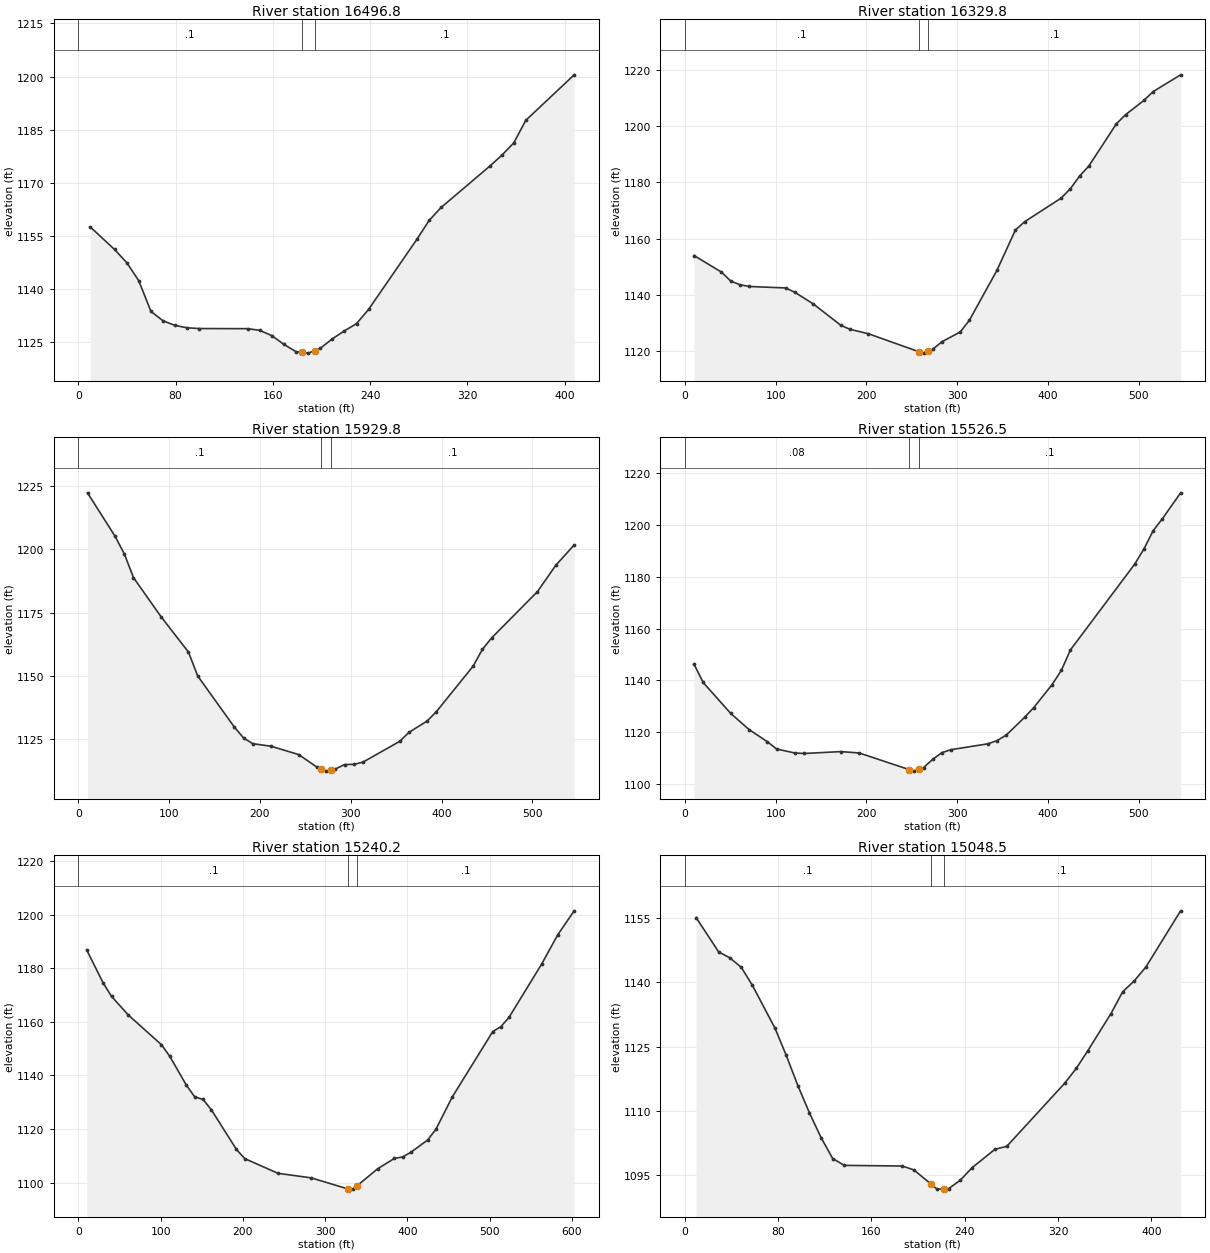
Type RM Length L Ch R = 1 ,16496.8 ,167.7,167,166.3
XS GIS Cut Line= 2
     1710984.709       194429.49     1710580.082      194480.386
#Sta/Elev= 30
     9.9 1157.47    29.8 1151.12    39.8 1147.42    49.7  1142.3    59.7 1133.64
    69.6 1130.98    79.6 1129.65    89.5 1128.99    99.5 1128.78   139.3 1128.74
   149.2 1128.27   159.1 1126.78   169.1  1124.3     179 1122.24   183.6 1122.05
     189 1121.83   194.4 1122.55   198.9 1123.16   208.9 1125.87   218.8 1128.11
   228.8 1130.17   238.7 1134.18   278.5 1154.02   288.5 1159.33   298.4 1163.01
   338.2 1174.62   348.1 1177.69   358.1 1181.24     368 1187.62   407.8 1200.49
#Mann= 3 , 0 , 0
       0      .1       0   183.6    .045       0   194.4      .1       0
Bank Sta=183.6,194.4
XS Rating Curve= 0 ,0
Exp/Cntr=0.3,0.1

Type RM Length L Ch R = 1 ,16329.8 ,402.2,400,397.8
XS GIS Cut Line= 3
     1711035.881      194245.604      1710766.31      194288.735
     1710496.739      194331.866
#Sta/Elev= 30
    10.1 1153.98    40.4 1148.08    50.6 1144.88    60.7  1143.6    70.8 1142.97
   111.2 1142.44   121.3 1140.87   141.6 1136.73   171.9 1129.14     182 1127.72
   202.2 1126.15   257.4 1119.79   262.9 1119.25   268.3 1119.98     273 1120.62
   283.1  1123.3   303.3 1126.77   313.4 1130.96   343.8 1148.75     364 1163.02
   374.1 1165.98   414.6 1174.44   424.7  1177.8   434.8 1182.28   444.9 1185.81
   475.2 1200.82   485.3 1204.06   505.6 1209.18   515.7  1212.3     546 1218.27
#Mann= 3 , 0 , 0
       0      .1       0   257.4    .045       0   268.3      .1       0
Bank Sta=257.4,268.3
XS Rating Curve= 0 ,0
Exp/Cntr=0.3,0.1

Type RM Length L Ch R = 1 ,15929.8 ,406.7,403.4,400.1
XS GIS Cut Line= 3
     1710929.758      193828.873     1710666.637      193901.651
     1710403.517      193974.429
#Sta/Elev= 30
    10.1 1222.36    40.4  1205.2    50.6 1198.23    60.7 1188.85      91  1173.4
   121.3 1159.36   131.4 1149.96   171.9 1129.66     182  1125.4   192.1 1123.14
   212.3 1122.13   242.7 1118.83   262.9 1113.84   267.5 1113.13     273 1112.29
   278.5 1112.75   283.1 1113.14   293.2 1114.89   303.3 1114.97   313.4 1115.84
   353.9 1124.07     364  1127.6   384.2 1132.14   394.3 1135.83   434.8 1153.84
   444.9  1160.4     455 1164.94   505.6 1183.29   525.8 1193.71     546 1201.72
#Mann= 3 , 0 , 0
       0      .1       0   267.5    .045       0   278.5      .1       0
Bank Sta=267.5,278.5
XS Rating Curve= 0 ,0
Exp/Cntr=0.3,0.1

Type RM Length L Ch R = 1 ,15526.5 ,294.8,286.3,277.9
XS GIS Cut Line= 3
     1710781.055      193409.681     1710533.489      193524.747
     1710285.923      193639.813
#Sta/Elev= 30
    10.1 1146.33    20.2 1139.21    50.6 1127.26    70.8 1121.02      91 1116.32
   101.1 1113.52   121.3 1111.98   131.4 1111.79   171.9 1112.52   192.1 1111.99
   247.2 1105.55   252.8 1104.98   258.3 1105.72   262.9 1106.35     273 1109.54
   283.1 1112.12   293.2 1113.27   333.7 1115.52   343.8 1116.76   353.9 1118.87
   374.1 1125.71   384.2  1129.5   404.4 1138.36   414.6 1143.85   424.7  1151.8
   495.4 1184.89   505.6 1190.77   515.7 1197.78   525.8 1202.37     546 1212.43
#Mann= 3 , 0 , 0
       0     .08       0   247.2    .045       0   258.3      .1       0
Bank Sta=247.2,258.3
XS Rating Curve= 0 ,0
Exp/Cntr=0.3,0.1

Type RM Length L Ch R = 1 ,15240.2 ,196.4,191.7,186.9
XS GIS Cut Line= 3
     1710595.351      193045.106     1710310.331      193373.388
     1710228.038      193519.869
#Sta/Elev= 30
    10.1 1186.85    30.3 1174.43    40.4 1169.49    60.7 1162.58   101.1 1151.45
   111.2 1147.14   131.4 1136.36   141.5 1132.04   151.7 1131.07   161.8 1127.18
   192.1 1112.49   202.2 1109.03   242.7 1103.53   283.1 1101.83   328.1 1097.67
   333.6 1097.63   339.2 1098.97     364 1105.24   384.2 1109.08   394.3 1109.63
   404.4 1111.39   424.6 1115.92   434.7 1119.93   454.5 1131.94   503.9 1156.39
   513.8 1158.23   523.7 1161.71   563.2 1181.51     583 1192.52   602.8 1201.39
#Mann= 3 , 0 , 0
       0      .1       0   328.1    .045       0   339.2      .1       0
Bank Sta=328.1,339.2
XS Rating Curve= 0 ,0
Exp/Cntr=0.3,0.1

Type RM Length L Ch R = 1 ,15048.5 ,209.9,217.5,225
XS GIS Cut Line= 3
     1710351.048      193012.023     1710282.338      193065.464
     1710127.104      193365.754
#Sta/Elev= 30
     9.7 1155.09      29 1147.09    38.7 1145.68    48.4 1143.49      58 1139.26
    77.4 1129.26      87 1122.94      97 1115.86   106.9 1109.52   116.9 1103.74
   126.8 1098.89   136.8  1097.3   186.5 1097.15   196.4 1096.24   210.7 1093.04
   216.3 1091.76   221.9 1091.82   226.2 1091.87   236.2 1093.84   246.1 1096.71
     266 1101.07     276 1101.73   325.7 1116.45   335.6  1119.9   345.5 1124.03
   365.4 1132.71   375.4 1137.78   385.3 1140.32   395.3 1143.55   425.1 1156.66
#Mann= 3 , 0 , 0
       0      .1       0   210.7    .045       0   221.9      .1       0
Bank Sta=210.7,221.9
XS Rating Curve= 0 ,0
Exp/Cntr=0.3,0.1

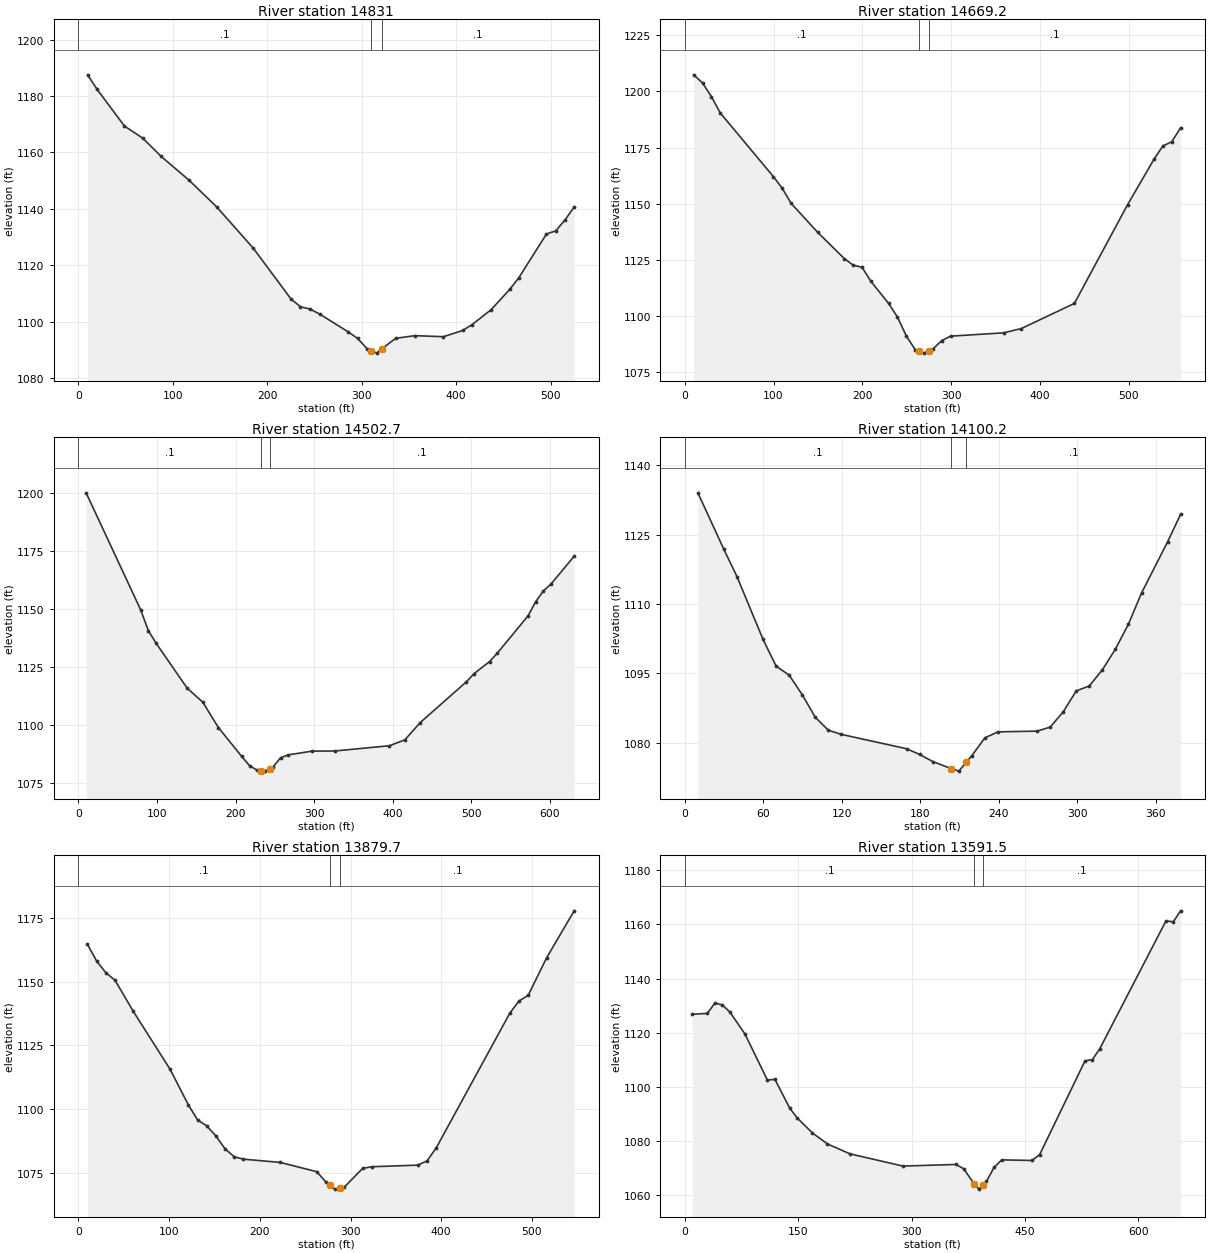
Type RM Length L Ch R = 1 ,14831   ,166.7,161.8,156.9
XS GIS Cut Line= 4
     1710312.896      192898.908     1710129.668      192990.522
      1709955.03      193143.688     1709936.421      193229.576
#Sta/Elev= 30
     9.8 1187.53    19.5 1182.56    48.8 1169.36    68.3 1165.04    87.8 1158.55
   117.1 1150.18   146.3 1140.74   185.3 1125.99   225.1 1108.02   235.2 1105.24
   245.3 1104.42   255.4 1102.67   285.7 1096.34   295.8 1093.98   305.9  1090.3
   310.3 1089.63   315.9 1088.78   321.6 1090.38   336.1 1094.04   356.3 1094.98
   386.6 1094.61   406.8 1096.81   416.9 1098.89   437.1 1104.19   456.7 1111.37
   466.4 1115.53   495.7 1131.05   505.5 1132.17   515.3 1136.03     525 1140.63
#Mann= 3 , 0 , 0
       0      .1       0   310.3    .045       0   321.6      .1       0
Bank Sta=310.3,321.6
XS Rating Curve= 0 ,0
Exp/Cntr=0.3,0.1

Type RM Length L Ch R = 1 ,14669.2 ,158.7,166.5,174.3
XS GIS Cut Line= 3
     1710135.763      192805.784     1709962.187      192904.634
     1709757.326      193199.358
#Sta/Elev= 30
      10 1207.32      20 1203.71      30 1197.63    39.9  1190.4    99.9 1162.04
   109.9 1156.82   119.8 1150.19   149.8 1137.29   179.8 1125.61   189.8 1122.69
   199.7 1121.78   209.7 1115.53   229.7 1105.69   239.6 1099.66   249.6 1091.25
   259.6 1085.16   263.9 1084.49   269.5 1083.61   275.2 1084.66   279.5 1085.45
   289.5 1089.18   299.5 1091.16   359.3 1092.63   379.2 1094.53     439 1105.71
   498.9 1149.57   528.8 1169.88   538.7  1175.7   548.7 1177.56   558.7 1183.81
#Mann= 3 , 0 , 0
       0      .1       0   263.9    .045       0   275.2      .1       0
Bank Sta=263.9,275.2
XS Rating Curve= 0 ,0
Exp/Cntr=0.3,0.1

Type RM Length L Ch R = 1 ,14502.7 ,413.4,402.6,391.8
XS GIS Cut Line= 3
     1710015.131      192709.189     1709691.939      192920.409
     1709451.631      192966.886
#Sta/Elev= 30
     9.9 1200.12    79.2 1149.72    89.1 1140.64      99 1135.19   138.6 1115.78
   158.4 1109.77   178.2 1098.84   207.9 1086.35   217.8 1082.41   227.7 1080.36
   231.9 1080.22   237.6 1080.03   243.3 1080.99   247.5  1081.7   257.4 1085.82
   267.3 1087.05     297 1088.64   326.7 1088.73   395.9 1090.99   415.5 1093.54
     435 1100.98   493.8 1118.57   503.6  1122.1   523.2 1127.28   532.9 1130.84
   572.1    1147   581.9 1153.11   591.7 1157.78   601.5 1160.78   630.9 1172.77
#Mann= 3 , 0 , 0
       0      .1       0   231.9    .045       0   243.3      .1       0
Bank Sta=231.9,243.3
XS Rating Curve= 0 ,0
Exp/Cntr=0.3,0.1

Type RM Length L Ch R = 1 ,14100.2 ,219.9,220.5,220.6
XS GIS Cut Line= 2
     1709574.877      192480.155     1709399.284      192816.072
#Sta/Elev= 30
      10 1134.03    29.9 1121.79    39.9 1115.91    59.8 1102.34    69.8 1096.56
    79.8  1094.6    89.8 1090.37    99.7 1085.52   109.7  1082.7   119.7  1081.8
   169.6  1078.7   179.5 1077.46   189.5 1075.94   203.7  1074.4   209.5 1073.86
   215.2 1075.79   219.4 1077.21   229.4 1081.06   239.4 1082.35   269.3 1082.51
   279.3 1083.38   289.3 1086.69   299.2  1091.2   309.2 1092.28   319.2 1095.77
   329.2 1100.27   339.1 1105.64   349.1 1112.36   369.1 1123.46     379  1129.4
#Mann= 3 , 0 , 0
       0      .1       0   203.7    .045       0   215.2      .1       0
Bank Sta=203.7,215.2
XS Rating Curve= 0 ,0
Exp/Cntr=0.3,0.1

Type RM Length L Ch R = 1 ,13879.7 ,293.8,288.2,282.9
XS GIS Cut Line= 3
     1709437.901      192308.271     1709295.227      192540.891
     1709166.829       192782.53
#Sta/Elev= 30
    10.1 1164.53    20.2 1158.03    30.3 1153.46    40.4 1150.52    60.6  1138.3
   101.1 1115.65   121.3 1101.68   131.4 1095.83   141.5 1093.46   151.6 1089.54
   161.7 1084.48   171.8 1081.39   181.9 1080.43   222.4 1079.16   262.8 1075.52
   272.9 1071.45   277.3 1070.25     283 1068.69   288.8 1069.15   293.2  1069.5
   313.4 1076.82   323.6 1077.46   374.2 1078.09   384.4 1079.75   394.5 1084.86
   475.6 1137.62   485.7 1142.38   495.8 1144.58   516.1 1159.27   546.5  1177.7
#Mann= 3 , 0 , 0
       0      .1       0   277.3    .045       0   288.8      .1       0
Bank Sta=277.3,288.8
XS Rating Curve= 0 ,0
Exp/Cntr=0.3,0.1

Type RM Length L Ch R = 1 ,13591.5 ,167.7,167.4,167.2
XS GIS Cut Line= 4
     1709141.422      192098.392     1709046.945      192338.877
     1708988.255      192593.678     1709028.336      192723.941
#Sta/Elev= 30
     9.9  1126.8    29.8 1127.13    39.8 1130.95    49.7 1130.25    59.6 1127.66
    79.5 1119.56   109.3  1102.5   119.3 1102.73   139.1 1091.99   149.1 1088.37
   168.9 1082.93   188.8 1078.88   218.6 1075.22   288.5  1070.7   358.9  1071.3
     369 1069.71   383.3 1063.99   389.1 1062.18   394.9 1063.81   399.2 1065.02
   409.2 1070.18   419.3    1073   459.5 1072.77   469.6 1074.95   529.6  1109.6
   539.3 1110.03   549.1 1114.04   636.7 1161.32   646.4    1161   656.1 1165.04
#Mann= 3 , 0 , 0
       0      .1       0   383.3    .045       0   394.9      .1       0
Bank Sta=383.3,394.9
XS Rating Curve= 0 ,0
Exp/Cntr=0.3,0.1

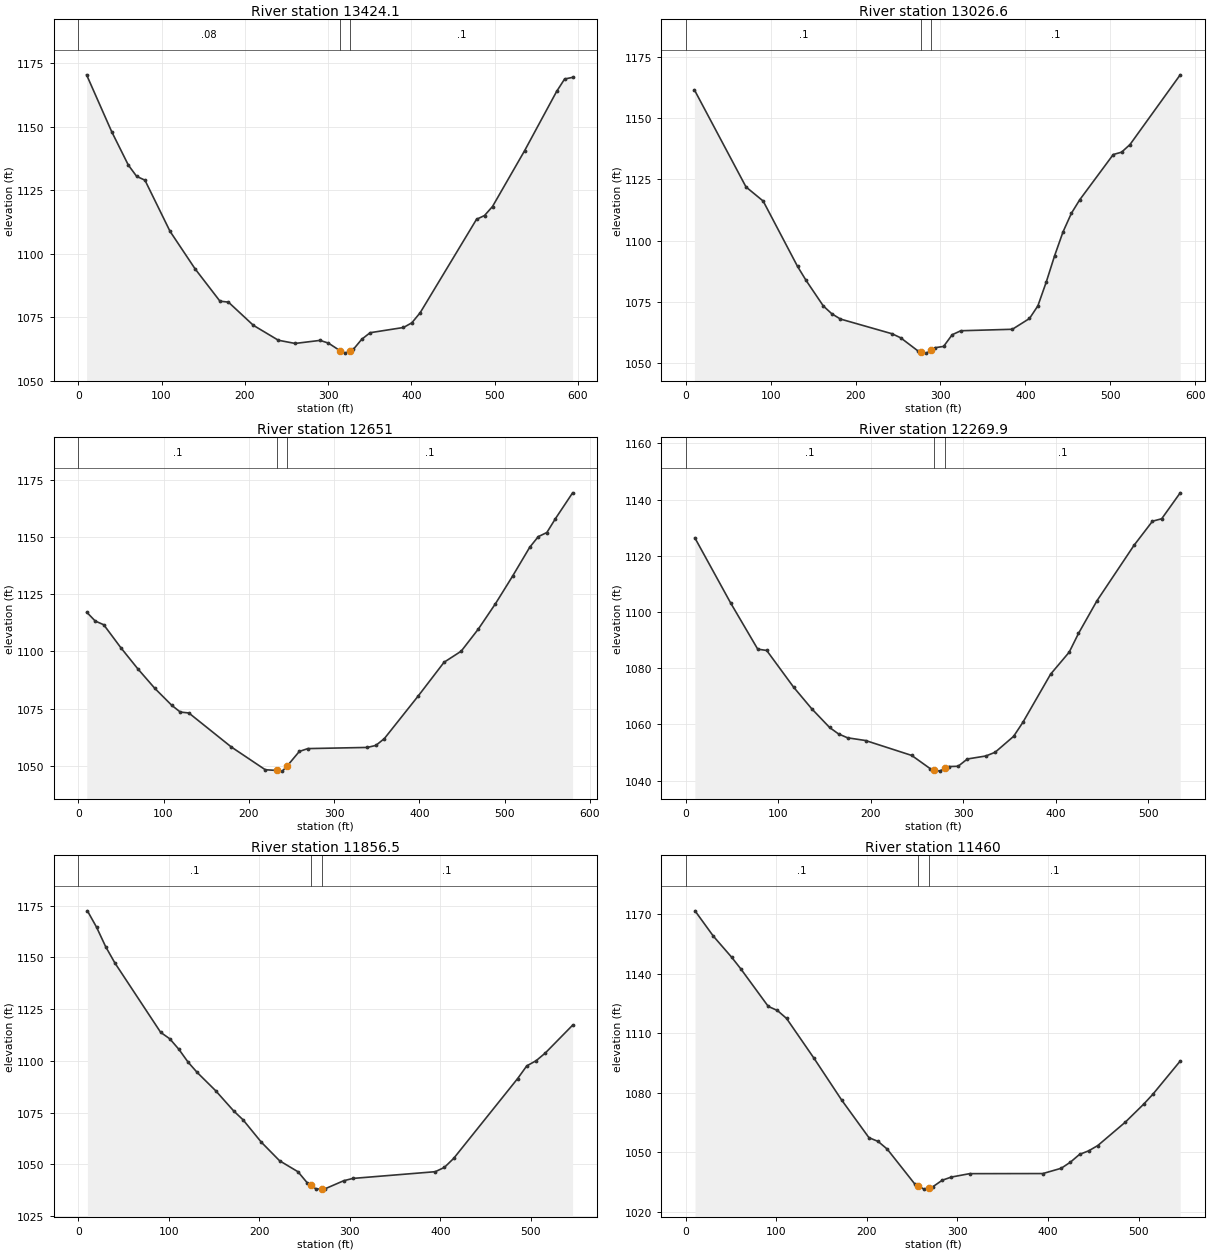
Type RM Length L Ch R = 1 ,13424.1 ,394.7,397.5,400.3
XS GIS Cut Line= 3
     1708925.271      192112.706     1708835.089      192523.536
      1708834.97      192696.633
#Sta/Elev= 30
      10 1170.37    40.1 1148.04    60.1 1134.89    70.1 1130.44    80.1 1128.92
   110.2 1108.82   140.2 1094.09   170.2 1081.32   180.3 1080.96   210.3 1071.83
   240.3 1065.96   260.4  1064.7   290.4  1065.9   300.4 1064.84   314.7 1061.78
   320.5 1060.89   326.3 1061.77   330.5 1062.42   340.5 1066.36   350.5 1068.92
   390.6 1070.98   400.6 1072.81   410.6 1076.77   478.3 1113.53   487.9 1115.02
   497.5 1118.57     536  1140.5   574.5 1163.84   584.1 1168.73   593.7 1169.37
#Mann= 3 , 0 , 0
       0     .08       0   314.7    .045       0   326.3      .1       0
Bank Sta=314.7,326.3
XS Rating Curve= 0 ,0
Exp/Cntr=0.3,0.1

Type RM Length L Ch R = 1 ,13026.6 ,384.4,375.6,366.7
XS GIS Cut Line= 3
     1708567.405       192076.92      1708425.69      192456.258
     1708473.953       192627.12
#Sta/Elev= 30
    10.1 1161.59    70.9 1121.91    91.1 1116.16   131.6 1089.43   141.7 1083.69
     162 1073.25   172.1 1070.04   182.2 1067.92     243  1061.9   253.1 1060.26
   273.3 1054.94   277.6 1054.54   283.5 1053.99   289.3 1055.26   293.6  1056.2
   303.7 1056.74   313.8 1061.51     324 1063.14   384.7 1063.74   404.9 1068.15
   414.8 1073.33   424.7  1083.1   434.5 1093.81   444.4 1103.55   454.3 1111.18
   464.1 1116.68   503.6 1135.18   513.4 1136.14   523.3 1139.25   582.5 1167.76
#Mann= 3 , 0 , 0
       0      .1       0   277.6    .045       0   289.3      .1       0
Bank Sta=277.6,289.3
XS Rating Curve= 0 ,0
Exp/Cntr=0.3,0.1

Type RM Length L Ch R = 1 ,12651   ,384.6,381.1,377.6
XS GIS Cut Line= 3
     1708102.179        191989.6     1708130.809      192397.568
     1708100.008      192565.652
#Sta/Elev= 30
      10 1117.11    19.9 1113.29    29.9 1111.65    49.9 1101.64    69.8 1092.42
    89.8 1083.85   109.7 1076.43   119.7 1073.48   129.7 1073.09   179.5 1058.23
   219.4 1048.26   233.5 1047.95   239.4 1047.66   245.3 1050.02   259.3 1056.26
   269.3 1057.51   339.1 1058.02   349.1  1058.9   359.1  1061.9     399 1080.62
   429.1 1095.26   449.2  1100.1   469.3 1109.77   489.4 1120.86   509.5 1132.92
   529.6 1145.54   539.6 1150.17   549.7 1151.98   559.7 1158.01   579.9 1169.33
#Mann= 3 , 0 , 0
       0      .1       0   233.5    .045       0   245.3      .1       0
Bank Sta=233.5,245.3
XS Rating Curve= 0 ,0
Exp/Cntr=0.3,0.1

Type RM Length L Ch R = 1 ,12269.9 ,420.6,413.4,406.3
XS GIS Cut Line= 3
     1707725.631      191998.675     1707724.273      192192.868
     1707804.435      192523.536
#Sta/Elev= 30
     9.7 1126.39    48.5 1103.14    77.7 1086.76    87.4 1086.29   116.5 1073.22
   135.9  1065.6   155.4 1058.87   165.1 1056.57   174.8  1055.2   194.2 1054.24
   244.2 1048.92   264.2 1044.21   268.3 1043.86   274.3 1043.34   280.2  1044.3
   284.3 1044.97   294.3 1045.07   304.3 1047.66   324.3 1048.73   334.3 1050.05
   354.3 1055.72   364.3  1060.7   394.3 1077.86   414.4 1085.69   424.4 1092.33
   444.4 1103.98   484.4 1123.69   504.4 1132.29   514.4 1133.18   534.4  1142.4
#Mann= 3 , 0 , 0
       0      .1       0   268.3    .045       0   280.2      .1       0
Bank Sta=268.3,280.2
XS Rating Curve= 0 ,0
Exp/Cntr=0.3,0.1

Type RM Length L Ch R = 1 ,11856.5 ,393,396.5,400
XS GIS Cut Line= 3
     1707205.789      192162.491     1707358.225      192388.968
     1707510.662      192615.446
#Sta/Elev= 30
    10.1  1172.5    20.2 1164.61    30.3 1155.16    40.4 1147.36      91 1113.81
   101.1 1110.68   111.2 1105.57   121.3 1099.41   131.4 1094.41   151.7 1085.64
   171.9 1075.73     182 1071.56   202.2 1060.74   222.4 1051.76   242.7 1046.46
   252.8 1041.16   256.9 1039.91   262.9 1038.07   268.9 1038.22     273 1038.31
   293.2 1042.13   303.3 1043.24   394.3 1046.49   404.4 1048.57   414.6  1052.9
   485.3 1091.49   495.4 1097.62   505.6 1100.07   515.7 1103.76     546 1117.26
#Mann= 3 , 0 , 0
       0      .1       0   256.9    .045       0   268.9      .1       0
Bank Sta=256.9,268.9
XS Rating Curve= 0 ,0
Exp/Cntr=0.3,0.1

Type RM Length L Ch R = 1 ,11460   ,397.9,399.3,400.8
XS GIS Cut Line= 3
     1706904.789      192335.817     1707015.334      192585.434
     1707125.879      192835.051
#Sta/Elev= 30
    10.1  1171.6    30.3 1158.88    50.6 1148.22    60.7 1142.37      91 1123.48
   101.1 1121.42   111.2 1117.42   141.6 1097.32   171.9 1076.44   202.2 1057.38
   212.3  1055.5   222.4 1051.62   252.8 1034.07   256.8 1033.04   262.9 1031.47
     269 1032.23     273 1032.73   283.1 1035.94   293.2 1037.54   313.4 1039.26
   394.3 1039.31   414.6 1041.98   424.7 1045.04   434.8 1048.96   444.9 1050.75
     455 1053.43   485.3 1065.17   505.6 1074.23   515.7  1079.2     546 1095.97
#Mann= 3 , 0 , 0
       0      .1       0   256.8    .045       0     269      .1       0
Bank Sta=256.8,269
XS Rating Curve= 0 ,0
Exp/Cntr=0.3,0.1