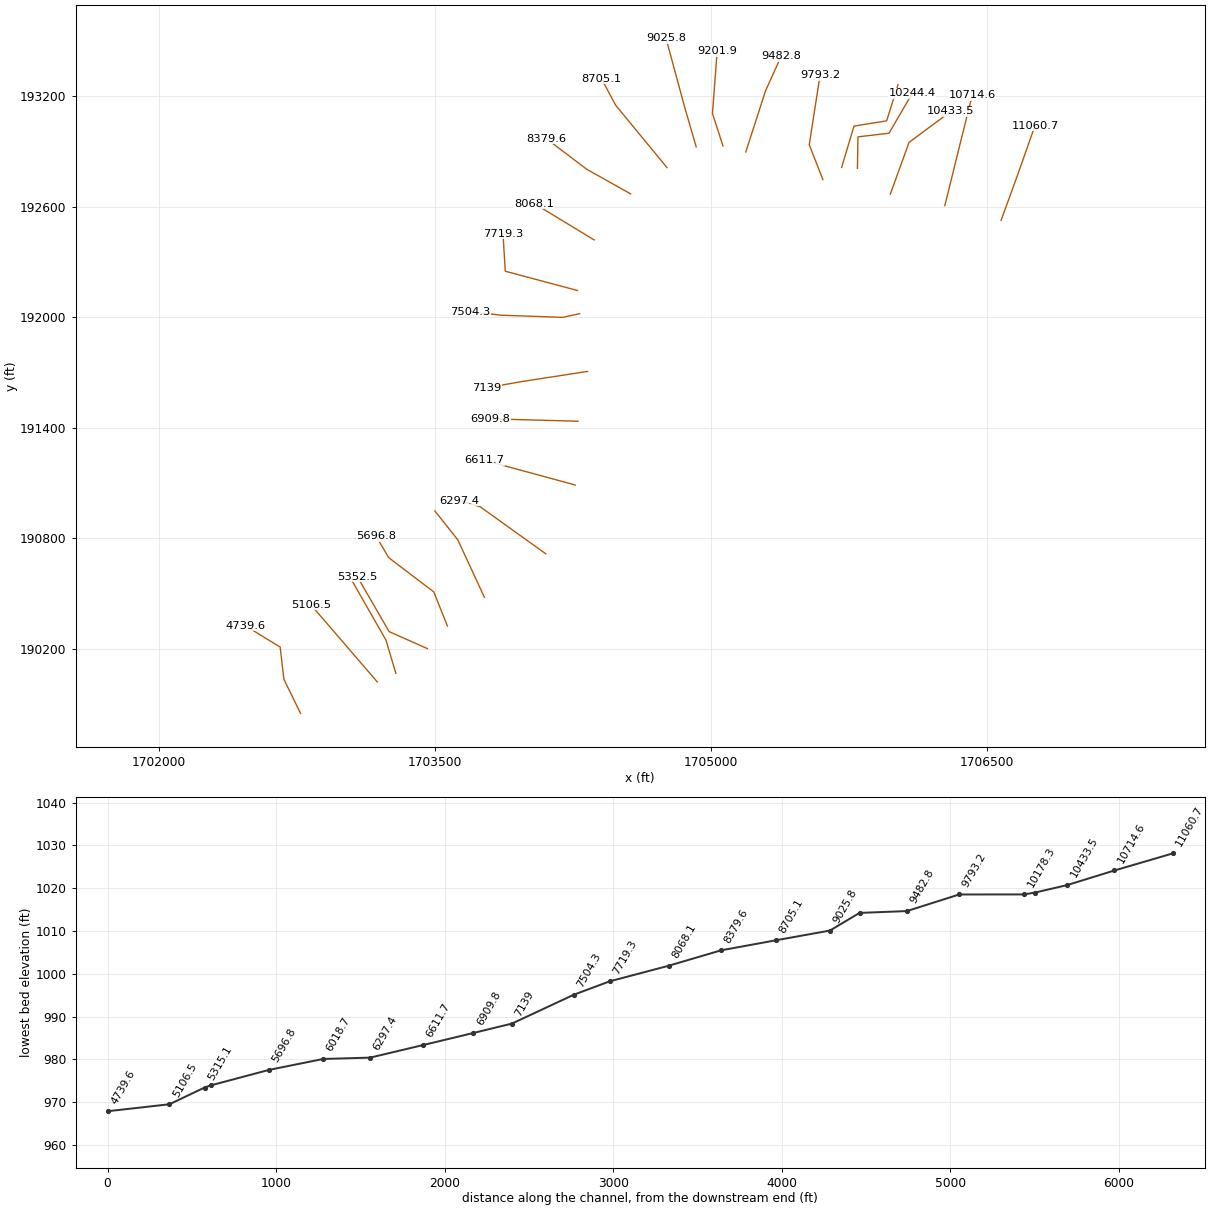
HEC-RAS study smsfrk.prj: smsfrk

--- smsfrk.g01 (geometry) --- (continued)

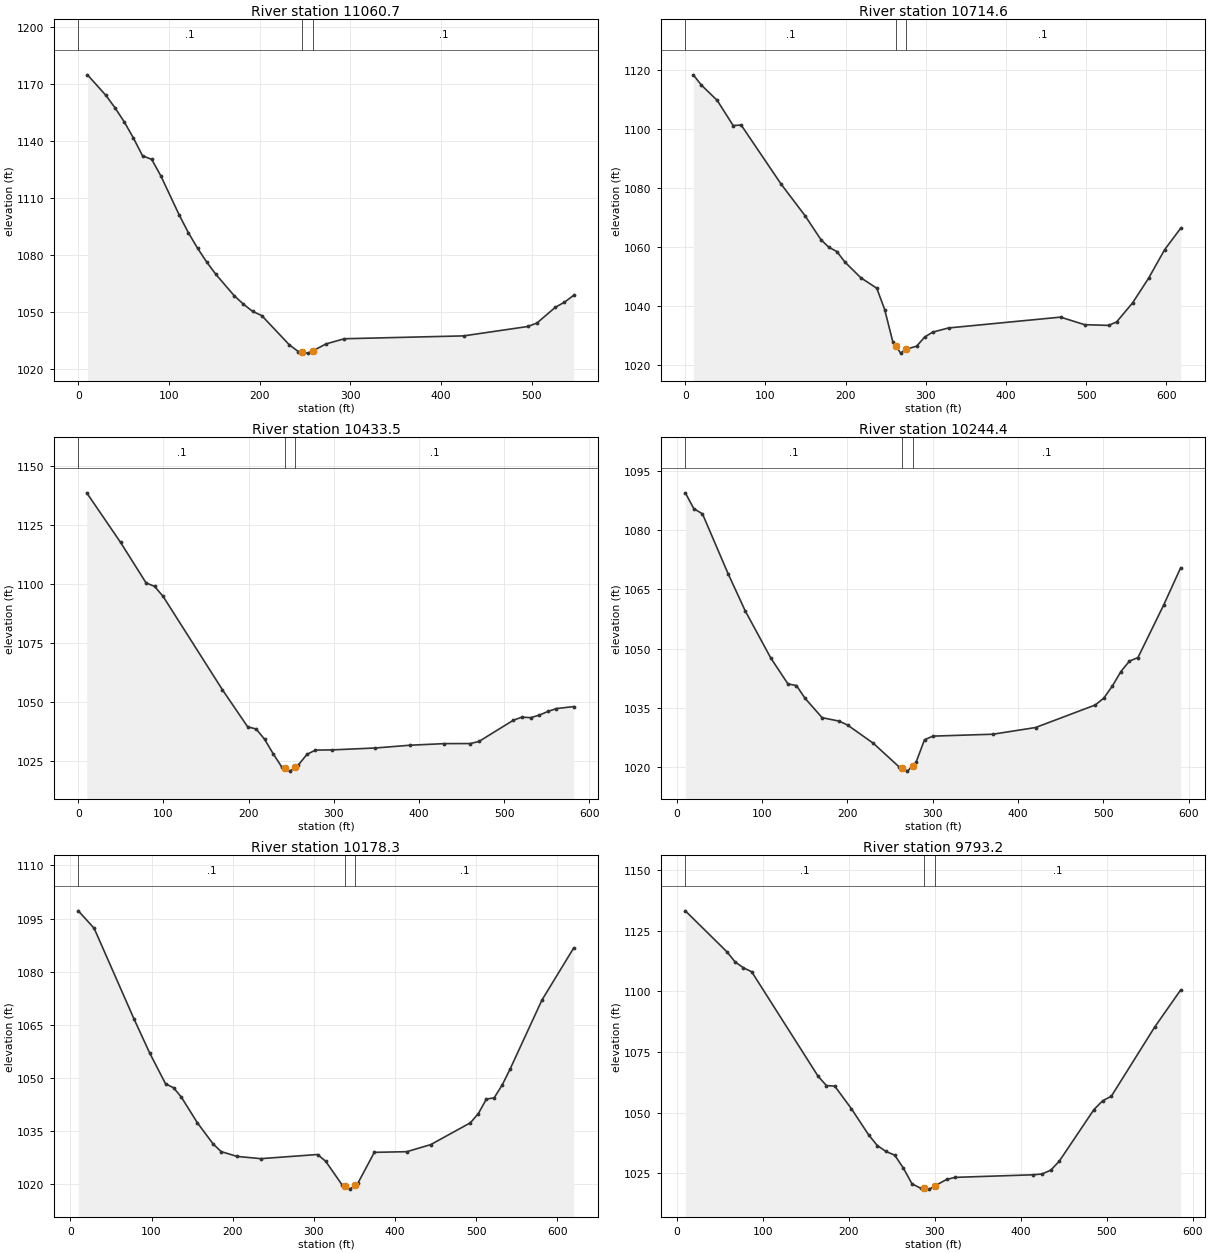
Type RM Length L Ch R = 1 ,11060.7 ,344,346.1,348.2
XS GIS Cut Line= 3
     1706578.486      192526.714     1706671.973       192783.23
     1706762.616      193040.739
#Sta/Elev= 30
    10.1 1174.87    30.3  1164.1    40.4 1157.52    50.6 1150.11    60.7 1141.59
    70.8 1132.19    80.9 1130.29      91 1121.58   111.2 1101.01   121.3 1091.66
   131.5 1083.42   141.6 1076.13   151.7 1069.65   171.9  1058.4     182 1053.97
   192.1 1050.18   202.2 1047.95   232.6 1032.52   242.7 1028.92   246.7 1028.61
   252.8 1028.15   258.9 1029.43     273    1033   293.2 1035.73   424.7 1037.24
   495.5 1042.19   505.6 1044.04   525.8 1052.31   535.9 1055.01     546 1058.63
#Mann= 3 , 0 , 0
       0      .1       0   246.7    .045       0   258.9      .1       0
Bank Sta=246.7,258.9
XS Rating Curve= 0 ,0
Exp/Cntr=0.3,0.1

Type RM Length L Ch R = 1 ,10714.6 ,283.3,281.1,278.9
XS GIS Cut Line= 3
     1706272.769      192606.561     1706358.657      192954.407
     1706421.641      193206.344
#Sta/Elev= 30
      10 1118.24    19.9 1114.81    39.8  1109.6    59.7  1101.1    69.7 1101.26
   119.4 1081.35   149.3 1070.66   169.2 1062.53   179.1 1059.94   189.1 1058.51
   199.1 1054.95     219 1049.64   238.9  1046.1   248.8 1038.84   258.8 1028.06
   262.6 1026.56   268.7 1024.16   274.9 1025.41   288.6 1026.52   298.6 1029.58
   308.5 1031.25   328.4 1032.67   468.2 1036.33   498.1 1033.78   528.1 1033.54
   538.1  1034.7   558.1 1041.18     578 1049.48     598 1059.12     618 1066.37
#Mann= 3 , 0 , 0
       0      .1       0   262.6    .045       0   274.9      .1       0
Bank Sta=262.6,274.9
XS Rating Curve= 0 ,0
Exp/Cntr=0.3,0.1

Type RM Length L Ch R = 1 ,10433.5 ,211.8,189.1,166.4
XS GIS Cut Line= 3
     1705976.456      192669.546      1706078.09      192950.112
     1706305.693      193119.025
#Sta/Elev= 30
     9.9 1138.59    49.7 1117.56    79.6 1100.45    89.5 1098.99    99.5 1094.78
   169.1 1055.29   198.9 1039.52   208.9 1038.58   218.8 1034.24   228.8 1028.15
   238.7 1022.63   242.5 1021.91   248.7 1020.74   254.9 1022.42   258.6 1023.42
   268.6 1027.86   278.5 1029.64   298.4 1029.74     349 1030.54   389.5 1031.71
     430 1032.39   460.4 1032.42   470.5 1033.29     511  1042.3   521.1  1043.6
   531.2 1043.38   541.4 1044.44   551.5 1046.01   561.6 1047.24   581.8 1048.06
#Mann= 3 , 0 , 0
       0      .1       0   242.5    .045       0   254.9      .1       0
Bank Sta=242.5,254.9
XS Rating Curve= 0 ,0
Exp/Cntr=0.3,0.1

Type RM Length L Ch R = 1 ,10244.4 ,65.3,66.1,67
XS GIS Cut Line= 4
     1705797.523      192809.829     1705800.386      192980.173
     1705969.299      193000.214     1706095.268      193216.365
#Sta/Elev= 30
      10 1089.36      20 1085.36    30.1 1084.05    60.1 1068.95    80.2 1059.54
   110.2  1047.6   130.3 1041.06   140.3 1040.64   150.3 1037.43   170.4 1032.52
   190.4 1031.65   200.4 1030.63   230.4 1026.05   260.4 1020.12   264.2  1019.7
   270.4 1019.01   276.6 1020.37   280.4 1021.21   290.4 1026.96   300.4 1027.86
   370.5 1028.34   420.5 1030.03   490.6 1035.74   500.6 1037.49   510.6 1040.54
   520.6 1044.19   530.6 1046.82   540.6 1047.73   570.6 1060.96   590.6 1070.42
#Mann= 3 , 0 , 0
      10      .1       0   264.2    .045       0   276.6      .1       0
#XS Ineff= 2 , 0
       0     230             285       0
Permanent Ineff=
       F       F
Bank Sta=264.2,276.6
XS Rating Curve= 0 ,0
Exp/Cntr=0.3,0.1

Type RM Length L Ch R = 1 ,10178.3 ,358.9,385,411.1
XS GIS Cut Line= 4
     1705711.636      192814.123     1705778.915      193038.863
     1705956.416      193067.492     1706017.969      193263.603
#Sta/Elev= 30
     9.8 1097.18    29.3 1092.25    78.2 1066.74    97.7 1057.02   117.3  1048.3
   127.1 1047.21   136.8 1044.52   156.4 1037.32   175.9 1031.31   185.7 1029.17
   205.3  1027.8   234.6 1027.17   304.5 1028.34   314.5 1026.43   334.5 1019.82
   338.2 1019.35   344.5 1018.56   350.7 1019.69   354.5 1020.39   374.4 1028.95
   414.4 1029.14   443.8 1031.13   492.7  1037.3   502.5 1039.89   512.3 1043.96
   522.1 1044.39   531.8 1047.95   541.6 1052.47   580.8 1071.96   619.9 1086.67
#Mann= 3 , 0 , 0
     9.8      .1       0   338.2    .045       0   350.7      .1       0
#XS Ineff= 2 , 0
       0     327             357       0
Permanent Ineff=
       F       F
Bank Sta=338.2,350.7
XS Rating Curve= 0 ,0
Exp/Cntr=0.3,0.1

Type RM Length L Ch R = 1 ,9793.2  ,313.6,310.4,307.2
XS GIS Cut Line= 3
     1705609.692      192748.452     1705535.566      192937.229
     1705594.289      193315.577
#Sta/Elev= 30
     9.7 1133.23    57.9 1116.42    67.6 1112.18    77.3 1109.75    86.9 1108.12
   164.2 1065.02   173.8 1061.23   183.5 1060.99   202.8 1051.71     223 1040.86
     233 1036.51   243.1 1034.06   253.2 1032.56   263.3  1027.2   273.3 1020.75
   283.4 1018.91   287.2  1018.9   293.5 1018.55   299.8 1019.87   313.6 1022.55
   323.7  1023.4   414.4 1024.46   424.5  1024.8   434.6 1026.34   444.6 1030.09
   484.9 1051.35     495 1054.96   505.1 1056.83   555.5 1085.33   585.7 1100.61
#Mann= 3 , 0 , 0
     9.7      .1       0   287.2    .045       0   299.8      .1       0
Bank Sta=287.2,299.8
XS Rating Curve= 0 ,0
Exp/Cntr=0.3,0.1

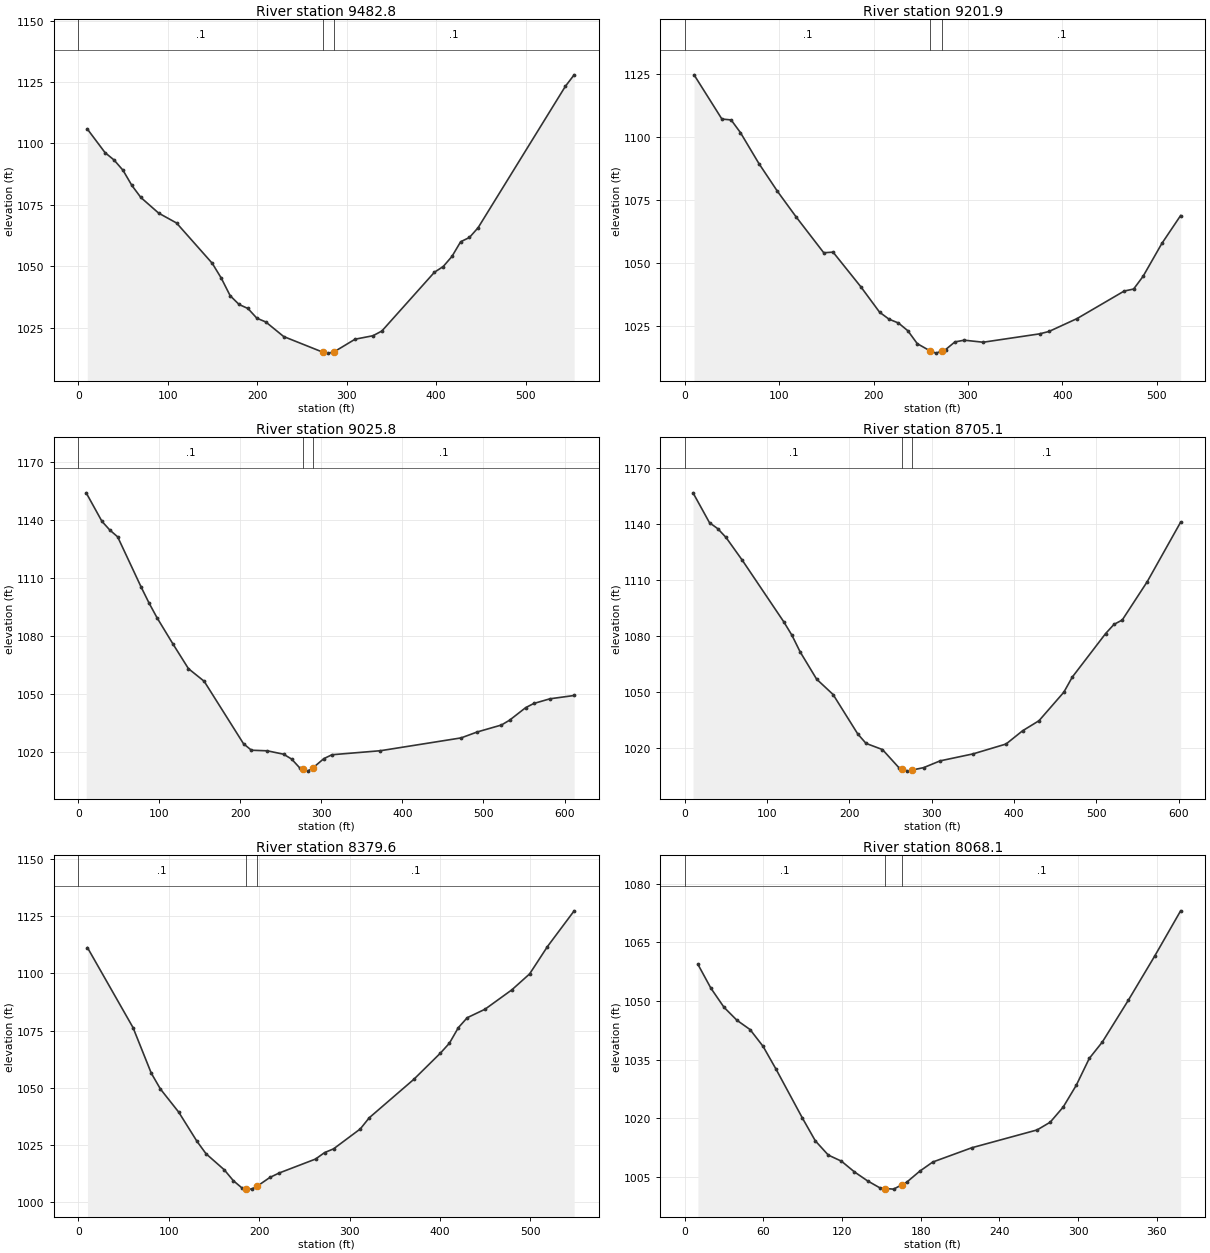
Type RM Length L Ch R = 1 ,9482.8  ,275.4,281,286.5
XS GIS Cut Line= 3
     1705190.574      192898.264     1705297.943      193230.679
     1705382.578      193417.369
#Sta/Elev= 30
      10 1105.91    29.9 1096.25    39.9 1093.28    49.9 1089.11    59.9 1082.89
    69.9 1078.01    89.8 1071.65   109.8 1067.63   149.7 1051.23   159.7 1045.26
   169.7 1038.06   179.7 1034.47   189.6 1032.84   199.6 1028.88   209.6 1027.35
   229.6 1021.41   273.1 1015.09   279.5 1014.67   285.8 1015.17   309.4 1020.34
   329.4 1021.75   339.3 1023.66   398.1 1047.59   407.9 1049.91   417.7 1054.03
   427.4    1060   437.2 1061.73   446.9  1065.7   544.5 1123.27   554.3 1127.93
#Mann= 3 , 0 , 0
       0      .1       0   273.1    .045       0   285.8      .1       0
Bank Sta=273.1,285.8
XS Rating Curve= 0 ,0
Exp/Cntr=0.3,0.1

Type RM Length L Ch R = 1 ,9201.9  ,169.1,176.1,183.1
XS GIS Cut Line= 3
     1705066.495      192930.679     1705009.237       193108.18
     1705035.003      193446.006
#Sta/Elev= 30
     9.8  1124.8    39.3 1107.24    49.1 1106.88    58.9 1101.88    78.5 1089.57
    98.2  1078.5   117.8 1068.43   147.2 1054.12   157.1 1054.36   186.5  1040.6
   206.4 1030.49   216.4 1027.72   226.4  1026.2   236.3 1023.13   246.3    1018
   259.9 1015.12   266.2 1014.24   272.6 1015.13   276.2 1015.62   286.2  1018.7
   296.1 1019.38   316.1 1018.57   375.8 1021.89   385.8 1022.84   415.7 1027.99
   465.5  1038.9   475.5  1039.7   485.5 1044.74   505.4  1057.8   525.3  1068.9
#Mann= 3 , 0 , 0
       0      .1       0   259.9    .045       0   272.6      .1       0
Bank Sta=259.9,272.6
XS Rating Curve= 0 ,0
Exp/Cntr=0.3,0.1

Type RM Length L Ch R = 1 ,9025.8  ,311.9,320.6,329.4
XS GIS Cut Line= 3
     1704920.861      192926.077     1704858.484      193140.497
      1704756.85       193515.54
#Sta/Elev= 30
     9.7 1153.99    29.1 1139.27    38.8 1134.77    48.5 1131.25    77.7 1105.11
    87.4 1096.91    97.1 1089.42   116.5 1076.03   135.9 1063.08   155.3 1056.57
   203.9 1024.25   213.6 1020.92   233.3 1020.61   253.2 1018.86   263.2 1016.36
   273.1 1011.85   276.7 1011.22   283.1 1010.11   289.5 1011.79     303 1016.58
     313 1018.58   372.8 1020.66   472.4 1027.29   492.3 1030.36   522.2 1033.96
   532.2 1036.45   552.1 1042.94   562.1 1045.09     582  1047.5   611.9 1049.22
#Mann= 3 , 0 , 0
       0      .1       0   276.7    .045       0   289.5      .1       0
Bank Sta=276.7,289.5
XS Rating Curve= 0 ,0
Exp/Cntr=0.3,0.1

Type RM Length L Ch R = 1 ,8705.1  ,318.1,325.5,333
XS GIS Cut Line= 3
     1704761.826      192813.564     1704482.009       193153.38
     1704406.141      193296.526
#Sta/Elev= 30
      10 1156.65      30 1140.68      40 1137.49      50 1132.83      70  1120.5
   120.1 1087.75   130.1 1080.52   140.1  1071.6   160.1 1057.03   180.1 1048.81
   210.1  1027.7   220.1 1022.68   240.1 1019.36   260.1 1009.66   263.7 1009.01
   270.1 1007.84   276.5 1008.46   290.1 1009.71   310.1 1013.33   350.2 1017.07
   390.2 1022.34   410.2  1029.4   430.2  1034.8   460.4 1050.07   470.6 1058.12
   511.1  1081.4   521.2 1086.28   531.3 1088.65   561.7 1109.18   602.2 1140.96
#Mann= 3 , 0 , 0
       0      .1       0   263.7    .045       0   276.5      .1       0
Bank Sta=263.7,276.5
XS Rating Curve= 0 ,0
Exp/Cntr=0.3,0.1

Type RM Length L Ch R = 1 ,8379.6  ,312.1,311.5,310.9
XS GIS Cut Line= 3
      1704564.38      192670.569     1704326.721      192803.802
     1704106.383      192970.141
#Sta/Elev= 30
    10.1 1111.34    60.5 1076.29    80.7  1056.3    90.8 1049.37     111 1039.26
   131.2 1026.47   141.3 1020.98   161.5 1013.94   171.5 1009.18   181.6 1005.81
   185.3 1005.69   191.7 1005.49   198.2 1006.87   211.9 1010.61     222 1012.53
   262.4 1018.67   272.5 1021.52   282.3 1023.13   311.9 1031.87   321.8 1036.76
   371.1  1053.6   400.6 1065.12   410.5 1069.45   420.4 1076.27   430.2 1080.61
   449.9 1084.34   479.5 1092.81   499.2  1099.8     519 1111.82   548.5 1127.46
#Mann= 3 , 0 , 0
       0      .1       0   185.3    .045       0   198.2      .1       0
Bank Sta=185.3,198.2
XS Rating Curve= 0 ,0
Exp/Cntr=0.3,0.1

Type RM Length L Ch R = 1 ,8068.1  ,343,348.7,354.5
XS GIS Cut Line= 2
      1704366.06      192420.471     1704042.549      192616.581
#Sta/Elev= 30
      10 1059.35    19.9 1053.25    29.9 1048.37    39.8 1045.04    49.8 1042.67
    59.7 1038.39    69.7 1032.49    89.6 1020.13    99.6 1014.22   109.5 1010.58
   119.5 1009.03   129.4 1006.29   139.4    1004   149.3 1002.12   152.8 1002.04
   159.3 1001.88   165.8 1003.02   169.2 1003.62   179.2 1006.45   189.2 1008.81
     219 1012.46   268.8 1017.01   278.8 1018.99   288.7 1022.86   298.7 1028.44
   308.6 1035.29   318.6  1039.5   338.5 1050.22   358.4 1061.39   378.3 1073.02
#Mann= 3 , 0 , 0
       0      .1       0   152.8    .045       0   165.8      .1       0
Bank Sta=152.8,165.8
XS Rating Curve= 0 ,0
Exp/Cntr=0.3,0.1

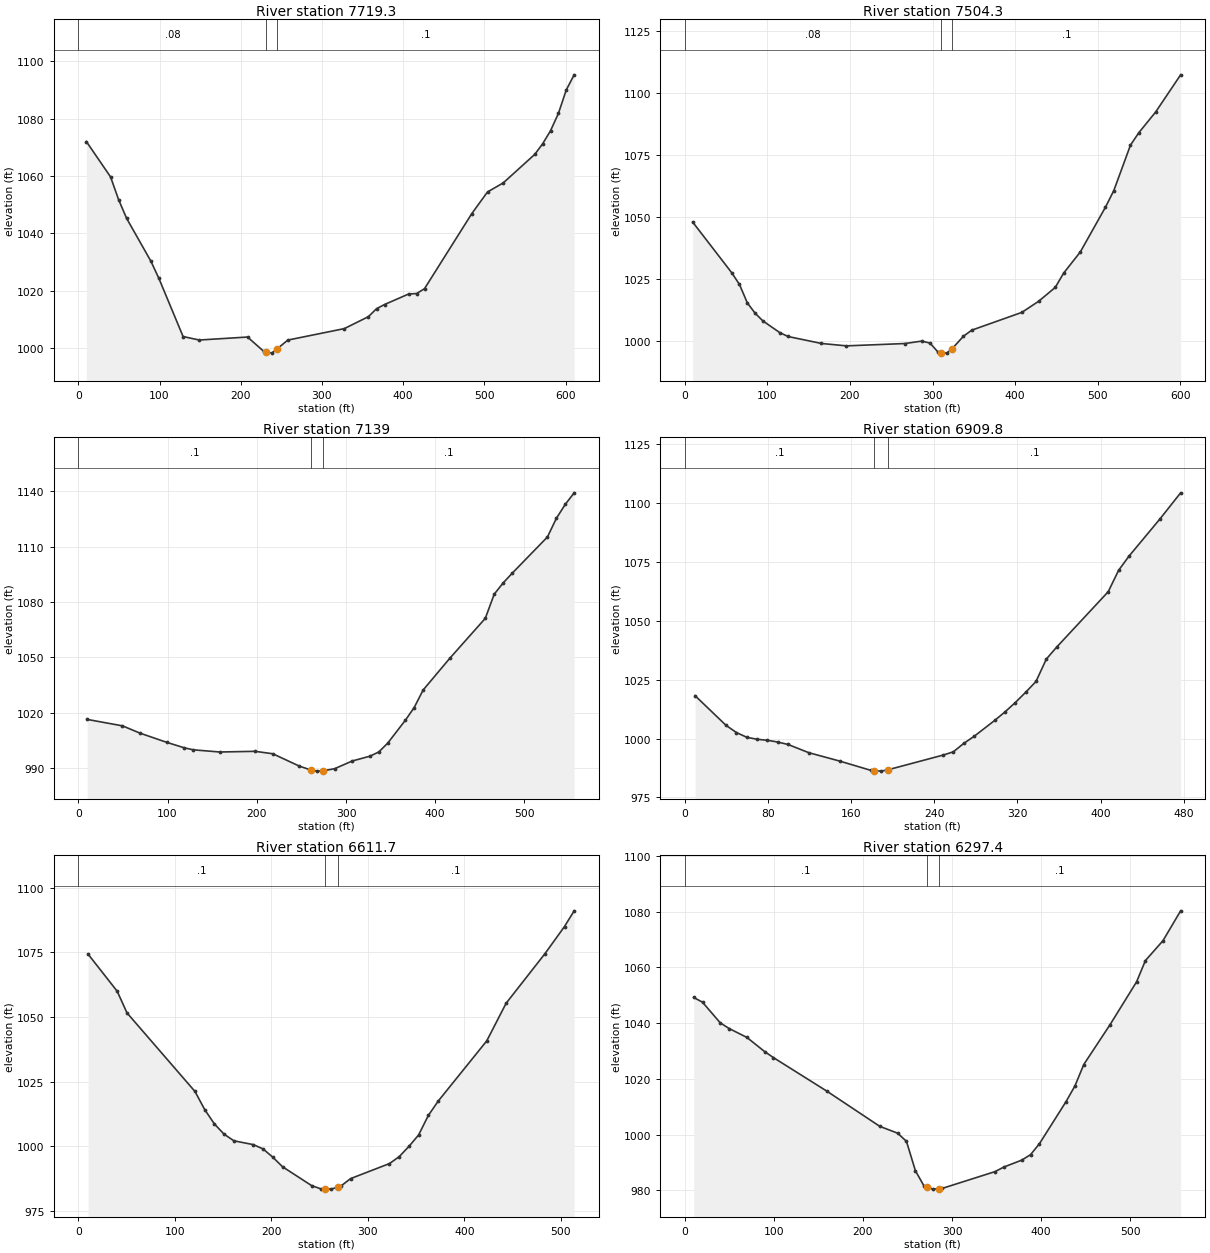
Type RM Length L Ch R = 1 ,7719.3  ,210.5,215,219.5
XS GIS Cut Line= 3
     1704275.878       192145.63     1703882.763      192250.455
     1703870.518      192453.846
#Sta/Elev= 30
     9.9 1072.02    39.7 1059.69    49.6 1051.75    59.5 1045.22    89.3 1030.33
    99.2 1024.31     129 1004.04   148.8 1002.82   208.4 1003.86   228.2   998.9
   231.6  998.68   238.2  998.25   244.7  999.71     258  1002.8   327.5 1006.79
   357.2 1010.96   367.2 1013.73   377.1  1015.2   406.9 1018.88   416.6 1019.02
   426.3 1020.71   484.5 1046.88   503.9 1054.44   523.3 1057.61   562.1 1067.55
   571.8 1071.24   581.5 1075.79   591.2 1081.81   600.9 1090.03   610.6 1095.28
#Mann= 3 , 0 , 0
       0     .08       0   231.6    .045       0   244.7      .1       0
Bank Sta=231.6,244.7
XS Rating Curve= 0 ,0
Exp/Cntr=0.3,0.1

Type RM Length L Ch R = 1 ,7504.3  ,361.4,365.4,369.4
XS GIS Cut Line= 4
      1704287.33      192019.661     1704194.822      191999.949
     1703861.291      192011.401      1703690.41      192031.113
#Sta/Elev= 30
     9.5 1047.97    56.8 1027.52    66.2 1022.78    75.7 1015.35    85.1 1011.21
    94.6 1008.07   114.8 1003.41   124.9  1001.8   165.4  998.99   195.7  998.02
   266.5  998.96   286.7  999.94   296.8  999.16     307  995.36   310.5  995.27
   317.1  995.09   323.6  996.85   337.3 1001.88   347.4 1004.35   408.1 1011.53
   428.3 1015.98   448.5 1021.59   458.7 1027.38   478.9 1035.92   509.3 1053.96
   519.4 1060.64   539.6    1079   549.7    1084     570 1092.32   600.3 1107.34
#Mann= 3 , 0 , 0
       0     .08       0   310.5    .045       0   323.6      .1       0
Bank Sta=310.5,323.6
XS Rating Curve= 0 ,0
Exp/Cntr=0.3,0.1

Type RM Length L Ch R = 1 ,7139    ,232.8,229.2,225.6
XS GIS Cut Line= 3
     1704330.274      191706.171     1703968.113      191650.344
      1703781.76      191617.168
#Sta/Elev= 30
     9.9 1016.41    49.5 1012.92    69.3 1008.93      99 1003.99   118.8 1001.01
   128.7  999.93   158.5  998.74   198.1  999.11   217.9  997.79   247.6  991.11
   260.8  988.94   267.4  988.37     274  988.52   287.2  989.67     307  993.87
   326.8  996.47   336.7  998.75   346.6 1003.46   366.4 1015.88   376.4 1022.83
   386.4 1032.33   416.2 1049.49   456.1 1071.22   466.1 1084.31     476 1090.35
     486 1095.55   525.8 1115.35   535.8 1125.48   545.8 1133.06   555.7 1139.27
#Mann= 3 , 0 , 0
       0      .1       0   260.8    .045       0     274      .1       0
Bank Sta=260.8,274
XS Rating Curve= 0 ,0
Exp/Cntr=0.3,0.1

Type RM Length L Ch R = 1 ,6909.8  ,302.9,298.1,293.2
XS GIS Cut Line= 2
     1704278.741      191435.624     1703802.064      191448.507
#Sta/Elev= 30
     9.9 1018.17    39.7 1005.57    49.7 1002.53    59.6 1000.53    69.5  999.68
    79.5  999.25    89.4  998.51    99.3  997.48   119.2     994     149  990.43
   178.8  986.52   182.1  986.41   188.8  986.17   195.4  986.74   248.4  992.97
   258.3  994.35   268.2   997.9   278.2  1000.9     298 1007.65     308  1011.3
   317.9 1015.26   327.8 1019.59   337.8 1024.21   347.7 1033.68   357.6 1038.74
   407.3  1062.3   417.2 1071.32   427.2 1077.34     457 1093.13   476.9 1104.22
#Mann= 3 , 0 , 0
       0      .1       0   182.1    .045       0   195.4      .1       0
Bank Sta=182.1,195.4
XS Rating Curve= 0 ,0
Exp/Cntr=0.3,0.1

Type RM Length L Ch R = 1 ,6611.7  ,321.5,314.3,307
XS GIS Cut Line= 2
     1704262.995       191089.21     1703767.099      191223.761
#Sta/Elev= 30
    10.1 1074.36    40.3 1059.97    50.4 1051.61   120.9 1021.16     131 1014.12
   141.1 1008.55   151.1 1004.61   161.2 1002.07   181.4 1000.58   191.4  998.92
   201.5  995.73   211.6  992.02   241.8   984.7   251.9  983.38   255.3  983.37
     262  983.35   268.6  984.11     272   984.5   282.1  987.42   322.4  993.24
   332.5  995.92   342.6   999.9   352.6 1004.33   362.7 1011.88   372.8 1017.39
   423.2 1040.75   443.3 1055.34   483.6 1074.57   503.8 1085.06   513.8 1091.13
#Mann= 3 , 0 , 0
       0      .1       0   255.3    .045       0   268.6      .1       0
Bank Sta=255.3,268.6
XS Rating Curve= 0 ,0
Exp/Cntr=0.3,0.1

Type RM Length L Ch R = 1 ,6297.4  ,289.1,278.7,268.4
XS GIS Cut Line= 3
     1704102.671      190715.598     1703746.774      190970.727
     1703633.004      191004.158
#Sta/Elev= 30
      10 1049.22    19.9 1047.52    39.8  1040.1    49.8 1038.07    69.7 1034.88
    89.6  1029.8    99.5 1027.63   159.2 1015.64   218.9 1002.94   238.9  1000.5
   248.8  997.56   258.8  987.03   268.7  981.42     272  981.09   278.7  980.41
   285.4  980.56   288.6  980.64   348.3  986.71   358.3  988.37   378.2  990.82
   388.1   992.8   398.1  996.75   427.9 1011.83   437.9 1017.48   447.8 1025.15
   477.4 1039.51   507.1 1054.86     517 1062.48   536.7 1069.61   556.5 1080.33
#Mann= 3 , 0 , 0
       0      .1       0     272    .045       0   285.4      .1       0
Bank Sta=272,285.4
XS Rating Curve= 0 ,0
Exp/Cntr=0.3,0.1

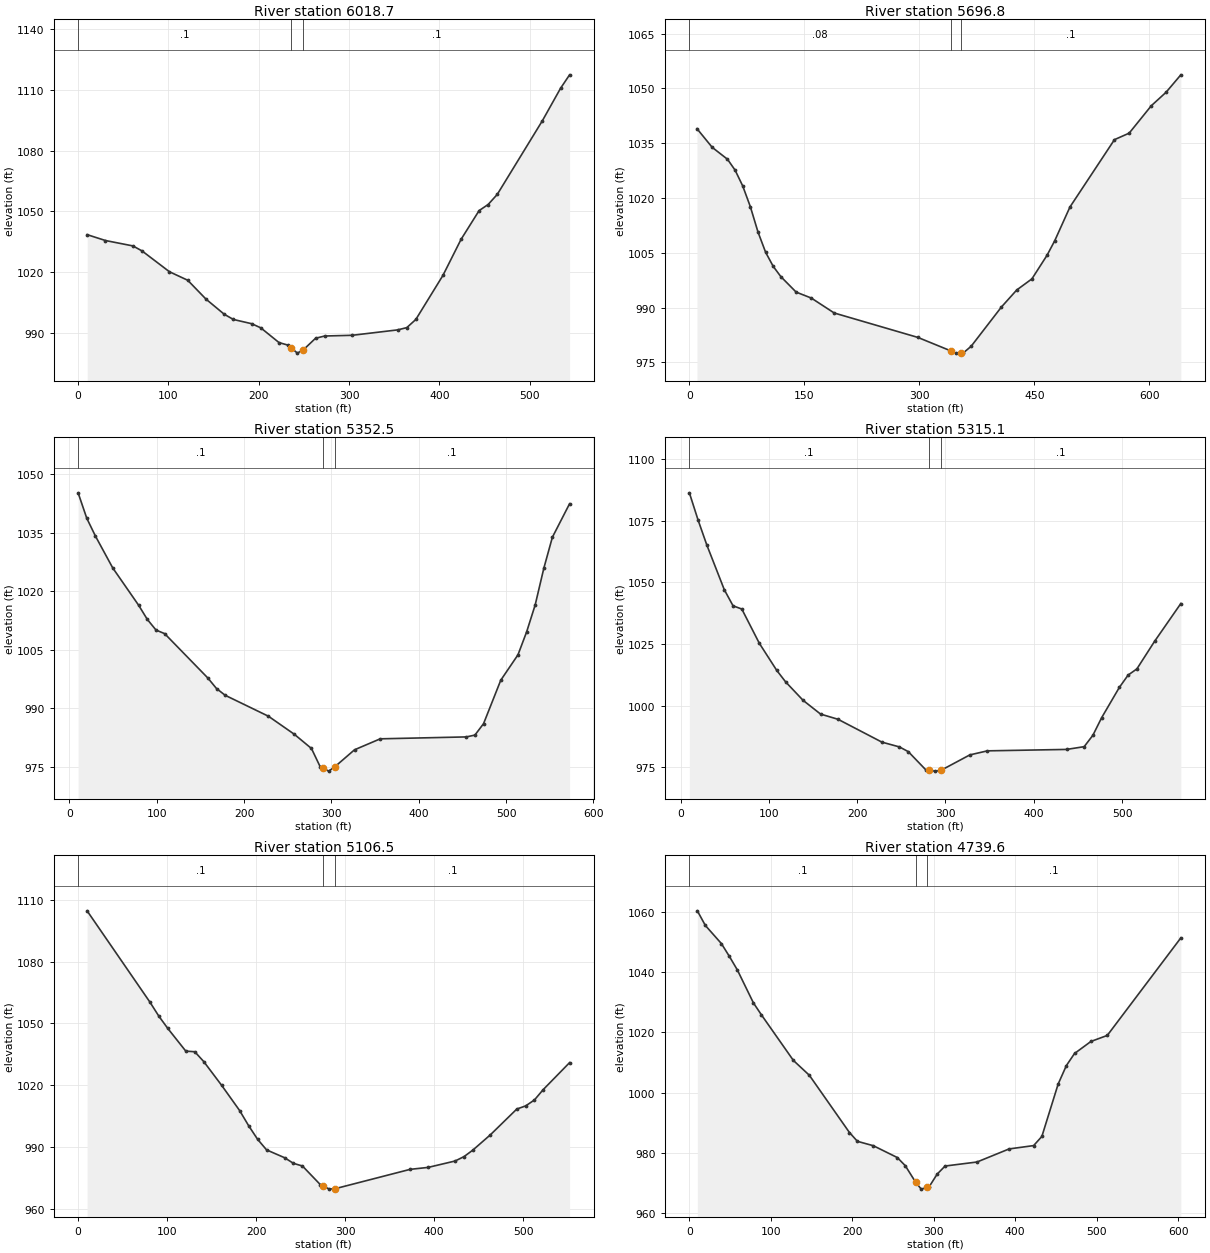
Type RM Length L Ch R = 1 ,6018.7  ,312.1,321.9,331.7
XS GIS Cut Line= 3
      1703769.14      190479.407     1703624.562      190791.466
     1703499.931      190948.373
#Sta/Elev= 30
    10.1  1038.5    30.3 1035.62    60.7 1032.96    70.8 1030.49   101.2 1020.21
   121.4 1016.03   141.6 1006.74   161.8  999.28     172  996.69   192.2  994.61
   202.3  992.57   222.5   985.3   232.7  984.01     236  982.73   242.8   980.1
   249.5  981.76     263  987.44   273.1  988.54   303.5  988.89   353.9  991.56
     364  992.67     374  996.69     404 1018.39   424.1 1036.19   444.1 1050.38
   454.1 1053.38   464.2 1058.36   514.2 1094.71   534.3 1110.69   544.3 1117.32
#Mann= 3 , 0 , 0
       0      .1       0     236    .045       0   249.5      .1       0
Bank Sta=236,249.5
XS Rating Curve= 0 ,0
Exp/Cntr=0.3,0.1

Type RM Length L Ch R = 1 ,5696.8  ,353.2,344.3,335.8
XS GIS Cut Line= 4
     1703568.244      190323.357     1703494.299      190508.036
     1703249.519      190694.126     1703180.809      190810.075
#Sta/Elev= 30
     9.9 1038.97    29.8 1033.85    49.7  1030.6    59.7  1027.6    69.6 1023.29
    79.6 1017.59    89.5  1010.7    99.5 1005.13   109.4 1001.28   119.4  998.46
   139.3  994.24   159.1  992.61     189  988.52   298.1  981.84   340.9  978.17
   347.7  977.54   354.5  977.61   357.6  977.64   367.6  979.41   407.2  990.18
   427.1  994.82   446.9  997.86   466.7 1004.34   476.7 1008.31   496.5 1017.52
   554.6 1035.96   573.8 1037.74   602.7 1045.25   621.9 1048.92   641.2  1053.7
#Mann= 3 , 0 , 0
       0     .08       0   340.9    .045       0   354.5      .1       0
Bank Sta=340.9,354.5
XS Rating Curve= 0 ,0
Exp/Cntr=0.3,0.1

Type RM Length L Ch R = 1 ,5352.5  ,37.6,37.5,37.3
XS GIS Cut Line= 3
     1703459.676      190200.271     1703251.398      190292.601
     1703078.548      190591.061
#Sta/Elev= 30
     9.9 1045.18    19.8 1038.68    29.7 1034.12    49.5 1025.97    79.2  1016.4
    89.1 1012.79    99.1 1010.05     109 1009.13   158.5  997.76   168.4  995.07
   178.3  993.35   227.8  987.99   257.4  983.38   277.1  979.73     287   975.1
     290  974.74   296.8  973.93   303.6  974.99   326.4  979.39   355.9   982.2
   454.5  982.69   464.3  983.16   474.2  986.09   493.9  997.21   513.6 1003.71
   523.5 1009.57   533.3 1016.48   543.2 1025.87     553 1033.81   572.7 1042.39
#Mann= 3 , 0 , 0
     9.9      .1       0     290    .045       0   303.6      .1       0
#XS Ineff= 2 , 0
       0     282             317       0
Permanent Ineff=
       F       F
Bank Sta=290,303.6
XS Rating Curve= 0 ,0
Exp/Cntr=0.3,0.1

Type RM Length L Ch R = 1 ,5315.1  ,204.8,208.6,212.3
XS GIS Cut Line= 3
       1703287.9      190066.072      1703234.22      190246.436
      1703046.34      190574.957
#Sta/Elev= 30
     9.9 1086.39    19.8  1075.3    29.7 1065.18    49.5 1047.03    59.4 1040.52
    69.3 1039.22    89.1 1025.34   108.9  1014.3   118.9 1009.66   138.7 1002.16
   158.5  996.58   178.3  994.46     228  985.19   247.9  983.24   257.9  981.32
   277.8  973.91   280.9  973.75   287.8  973.42   294.6  973.69   327.6  980.01
   347.5  981.65   437.2  982.23   457.1  983.35     467  987.99     477  995.18
   496.9 1007.38   506.9 1012.42   516.8 1014.91   536.8 1026.08   566.6 1041.46
#Mann= 3 , 0 , 0
     9.9      .1       0   280.9    .045       0   294.6      .1       0
#XS Ineff= 2 , 0
       0     278             300       0
Permanent Ineff=
       F       F
Bank Sta=280.9,294.6
XS Rating Curve= 0 ,0
Exp/Cntr=0.3,0.1

Type RM Length L Ch R = 1 ,5106.5  ,378.9,366.9,354.9
XS GIS Cut Line= 3
     1703186.549      190019.843     1702903.552      190348.428
      1702825.59      190437.877
#Sta/Elev= 30
    10.1 1104.65    80.7 1060.32    90.8 1053.45   100.8 1047.53     121 1036.53
   131.1 1036.22   141.2 1031.44   161.4 1019.85   181.5 1007.67   191.6 1000.33
   201.7  993.71   211.8  988.56     232  984.77     242  982.03   252.1  980.74
   272.3  971.64   275.5  970.96   282.4  969.51   289.2  969.76   373.1  979.11
   393.3  980.06   423.6  983.16   433.7  985.31   443.5  988.43   463.3  995.89
     493 1008.41   502.9 1009.91   512.8 1012.81   522.6 1017.81   552.3 1030.94
#Mann= 3 , 0 , 0
       0      .1       0   275.5    .045       0   289.2      .1       0
Bank Sta=275.5,289.2
XS Rating Curve= 0 ,0
Exp/Cntr=0.3,0.1

Type RM Length L Ch R = 1 ,4739.6  ,295.1,311.1,327.1
XS GIS Cut Line= 4
     1702769.714      189848.517      1702679.17      190033.864
     1702658.772       190208.86     1702470.158      190323.756
#Sta/Elev= 30
     9.8 1060.44    19.6 1055.58    39.3 1049.55    49.1 1045.29    58.9 1040.78
    78.6 1029.83    88.4 1025.86   127.7 1010.68   147.3 1005.74   196.5  986.71
   206.3  983.78   225.9  982.31   255.2  978.39     265  975.69   277.7   970.2
   284.6  967.88   291.5  968.45   294.4  968.69   304.2  972.88   313.9  975.56
   353.1   976.9   392.5  981.25   422.6  982.36   432.7   985.4   452.7 1002.83
   462.8 1008.98   472.8 1012.99   492.9 1016.99     513    1019   603.3 1051.44
#Mann= 3 , 0 , 0
       0      .1       0   277.7    .045       0   291.5      .1       0
Bank Sta=277.7,291.5
XS Rating Curve= 0 ,0
Exp/Cntr=0.3,0.1