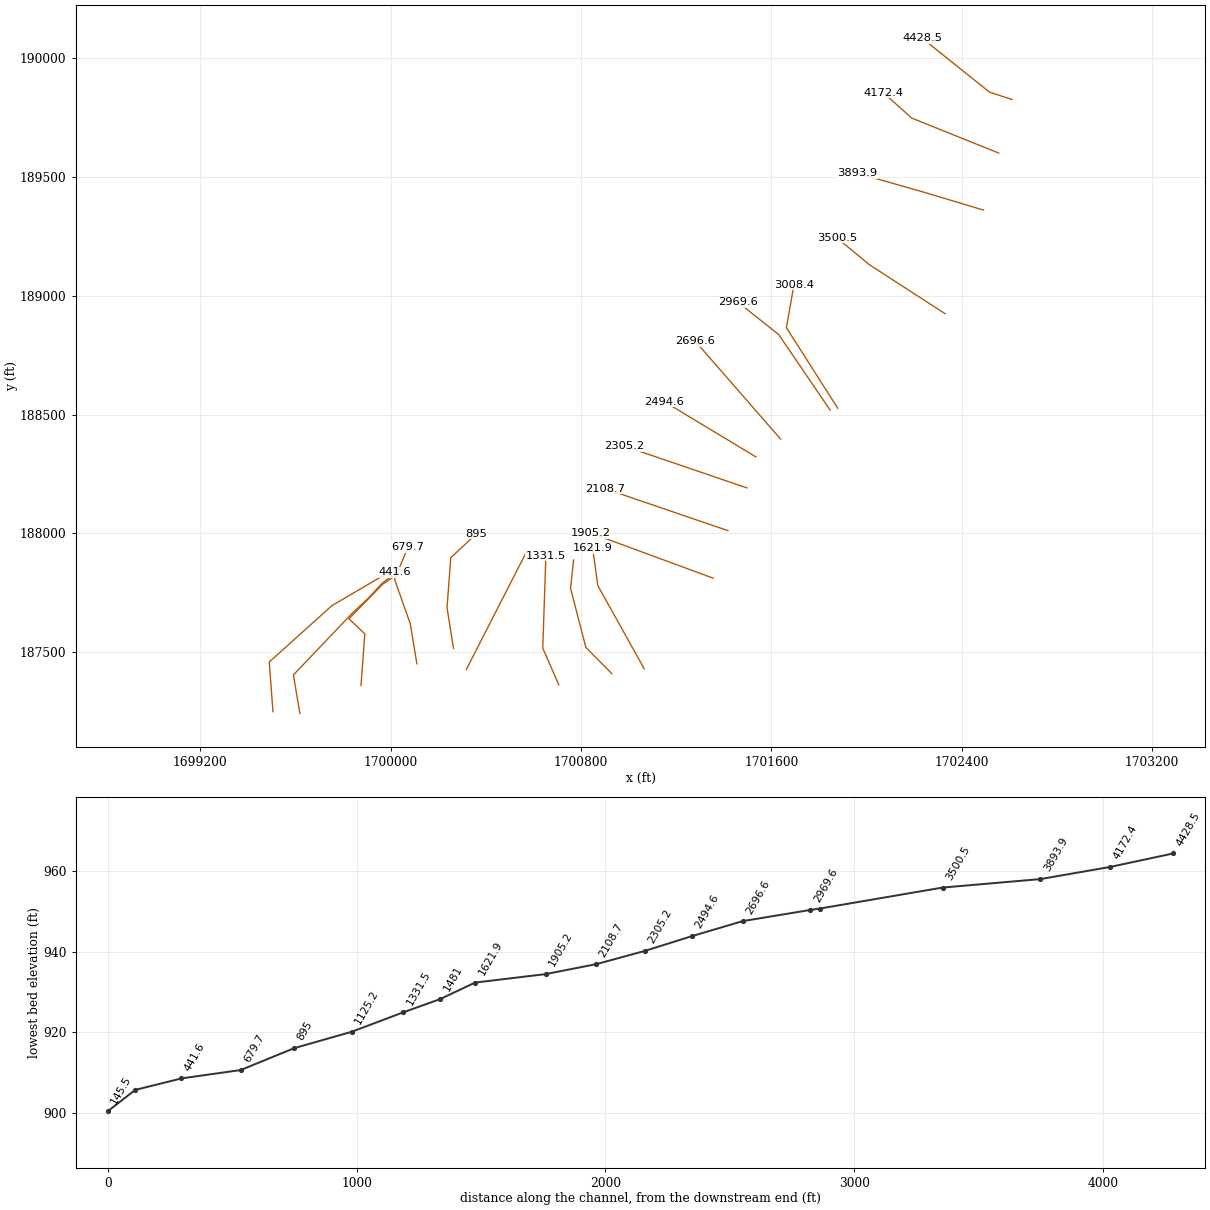
HEC-RAS study smsfrk.prj: smsfrk

--- smsfrk.g01 (geometry) --- (continued)

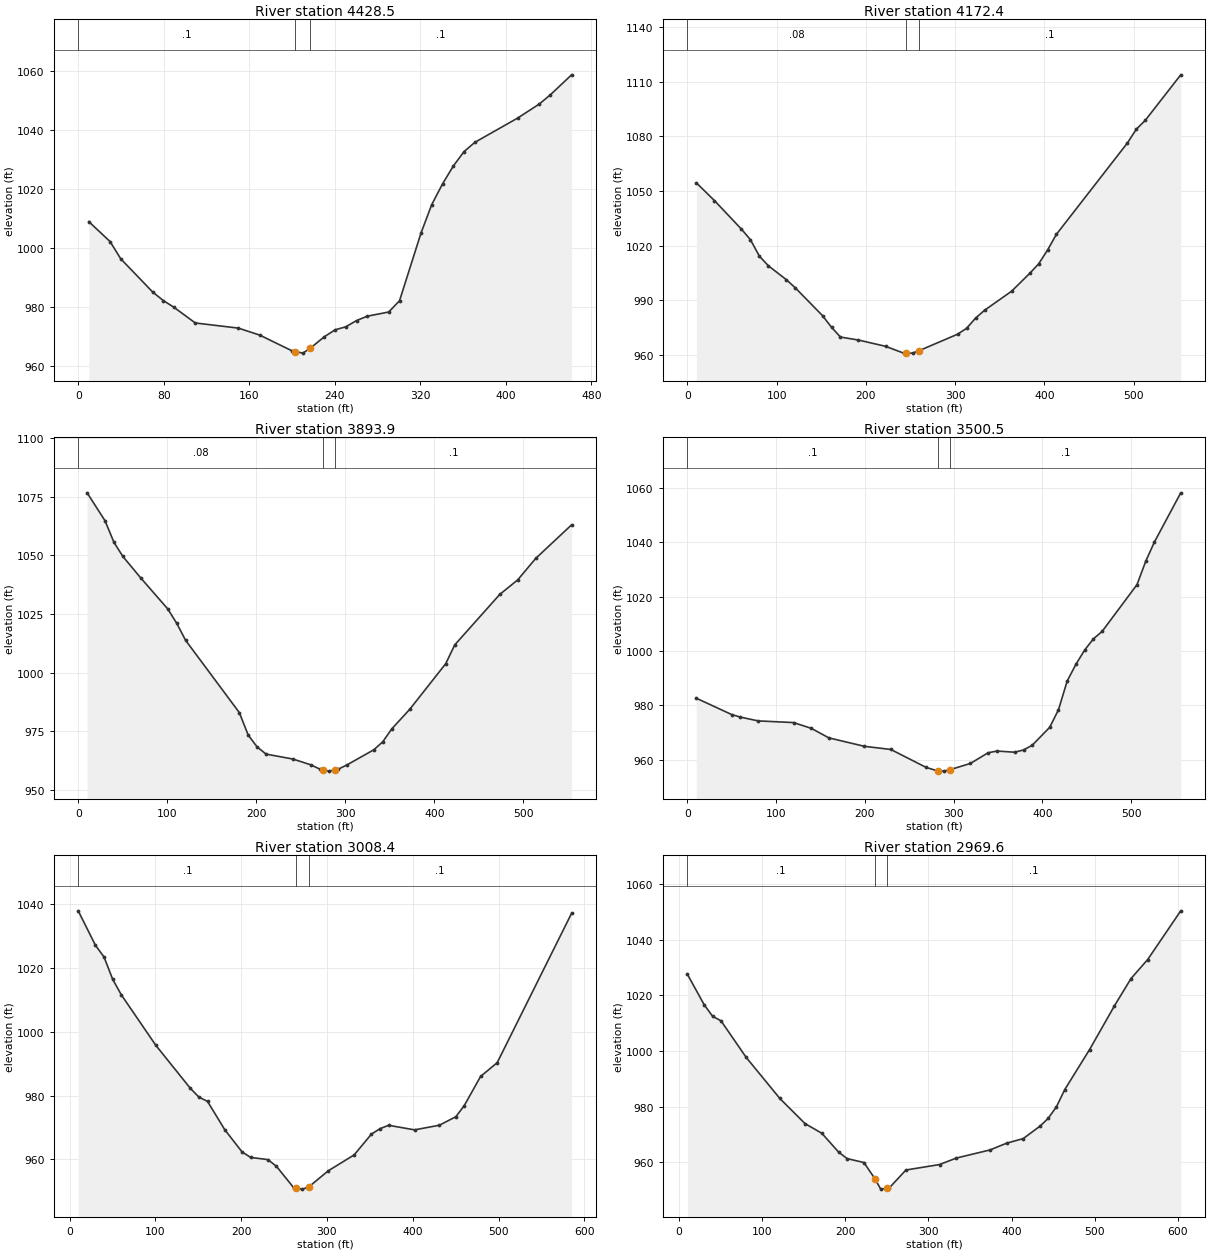
Type RM Length L Ch R = 1 ,4428.5  ,250.2,256.1,262
XS GIS Cut Line= 3
     1702611.534      189826.659     1702517.057      189857.794
     1702234.701      190084.323
#Sta/Elev= 30
     9.9 1008.89    29.8 1002.12    39.8  996.26    69.6  985.02    79.6   982.1
    89.5  979.84   109.5   974.5   149.8  972.76   169.9  970.37     200  965.05
   203.1  964.81   210.1  964.27     217  965.91   230.2  969.82   240.3  972.18
   250.3   973.2   260.4  975.33   270.4   976.8   290.5  978.22   300.6  982.07
   320.7 1005.05   330.7 1014.66   340.8 1021.68   350.9 1027.75   360.9 1032.63
     371 1035.77   411.2 1044.04   431.3 1048.78   441.4 1051.81   461.5 1058.68
#Mann= 3 , 0 , 0
       0      .1       0   203.1    .045       0     217      .1       0
Bank Sta=203.1,217
XS Rating Curve= 0 ,0
Exp/Cntr=0.3,0.1

Type RM Length L Ch R = 1 ,4172.4  ,276.6,278.5,280.7
XS GIS Cut Line= 3
     1702555.706      189601.204     1702190.683      189748.287
     1702071.974      189854.437
#Sta/Elev= 30
    10.1 1054.43    30.3  1044.7    60.5 1029.04    70.6 1023.23    80.7 1014.15
    90.8 1008.85     111 1001.21   121.1  996.66   151.4   981.5   161.5   975.1
   171.5  969.73   191.7  968.09     222  964.65   242.2  960.92   245.3  960.91
   252.3   960.9   259.2  962.17   302.7  971.28   312.8  974.51   322.9  980.13
     333  984.46   363.3  994.92   383.5 1004.67   393.5 1009.88   403.5 1017.46
   413.4 1026.11   493.1 1076.38     503 1083.89     513 1088.74   552.8 1113.77
#Mann= 3 , 0 , 0
       0     .08       0   245.3    .045       0   259.2      .1       0
Bank Sta=245.3,259.2
XS Rating Curve= 0 ,0
Exp/Cntr=0.3,0.1

Type RM Length L Ch R = 1 ,3893.9  ,399,393.4,387.5
XS GIS Cut Line= 3
     1702492.062      189361.102     1702232.228      189439.054
     1701960.267      189516.489
#Sta/Elev= 30
      10 1076.72    30.1 1064.81    40.2 1055.54    50.2 1049.54    70.3 1040.35
   100.5 1027.19   110.5 1021.11   120.6 1013.76   180.9  982.92   190.9   973.3
   200.9  968.25     211  965.18   241.1  963.08   261.2  960.61   271.3  958.79
   274.4  958.52   281.4  957.92   288.4  958.42   291.5  958.64   301.6  960.54
   331.9  967.02     342  970.45   352.1  975.96   372.3  984.32   412.7  1003.8
   422.8  1011.8   473.3 1033.33   493.5 1039.55   513.7 1048.71     554 1063.05
#Mann= 3 , 0 , 0
       0     .08       0   274.4    .045       0   288.4      .1       0
Bank Sta=274.4,288.4
XS Rating Curve= 0 ,0
Exp/Cntr=0.3,0.1

Type RM Length L Ch R = 1 ,3500.5  ,500.7,492.1,483.5
XS GIS Cut Line= 3
     1702330.251      188924.837     1702012.466      189130.968
     1701875.887       189243.82
#Sta/Elev= 30
      10  982.67    49.8  976.66    59.8   975.7    79.7  974.31   119.6  973.69
   139.6  971.57   159.5  968.05   199.4  964.96   229.3  963.79   269.1  957.18
     282  955.89   289.1  955.82   296.1  956.36     319  958.66   338.9  962.58
   348.9  963.21   368.8  962.78   378.8  963.61   388.6  965.34   408.3  971.94
   418.2   978.4     428  988.96   437.8   995.1   447.7 1000.38   457.5 1004.48
   467.4 1007.24   506.7 1024.46   516.6 1033.11   526.4  1040.2     556 1058.25
#Mann= 3 , 0 , 0
       0      .1       0     282    .045       0   296.1      .1       0
Bank Sta=282,296.1
XS Rating Curve= 0 ,0
Exp/Cntr=0.3,0.1

Type RM Length L Ch R = 1 ,3008.4  ,38.2,38.8,39.4
XS GIS Cut Line= 3
      1701879.34      188526.533     1701663.547       188865.79
     1701695.243      189046.004
#Sta/Elev= 30
    10.1 1037.93    30.2 1027.12    40.2 1023.44    50.3 1016.44    60.3  1011.6
   100.5  995.77   140.7  982.29   150.8   979.5   160.8  978.16   180.9  969.28
     201  962.33   211.1  960.58   231.2   959.9   241.2  957.78   261.3  951.06
   264.3  950.94   271.4  950.64   278.5  951.27   301.6   956.4   331.7  961.37
   351.8  967.88   361.9  969.61   371.9  970.66   402.1  969.23     431  970.68
   450.2  973.35   459.9  976.78   479.1     986   498.4  990.29   585.1 1037.15
#Mann= 3 , 0 , 0
    10.1      .1       0   264.3    .045       0   278.5      .1       0
#XS Ineff= 2 , 0
       0     255             290       0
Permanent Ineff=
       F       F
Bank Sta=264.3,278.5
XS Rating Curve= 0 ,0
Exp/Cntr=0.3,0.1

Type RM Length L Ch R = 1 ,2969.6  ,270.6,273,275.4
XS GIS Cut Line= 3
     1701847.132      188519.018     1701631.339      188836.803
     1701459.563      188973.149
#Sta/Elev= 30
    10.1 1027.62    30.3 1016.64    40.4 1012.49    50.5 1010.87    80.9  997.66
   121.3  982.91   151.6  973.86   171.8  970.39   192.1  963.57   202.2  961.28
   222.4  959.86   235.5  954.09   242.6  950.29   249.7  950.56   252.7  950.67
   272.9  957.17   313.4  959.14   333.6  961.48     374  964.39   394.1  966.83
     414  968.48     434  972.92   443.9  975.73   453.9  979.91   463.9   986.1
   493.8 1000.53   523.7 1016.27   543.6 1026.07   563.6  1032.9   603.4 1050.44
#Mann= 3 , 0 , 0
    10.1      .1       0   235.5    .045       0   249.7      .1       0
#XS Ineff= 2 , 0
       0     235             258       0
Permanent Ineff=
       F       F
Bank Sta=235.5,249.7
XS Rating Curve= 0 ,0
Exp/Cntr=0.3,0.1

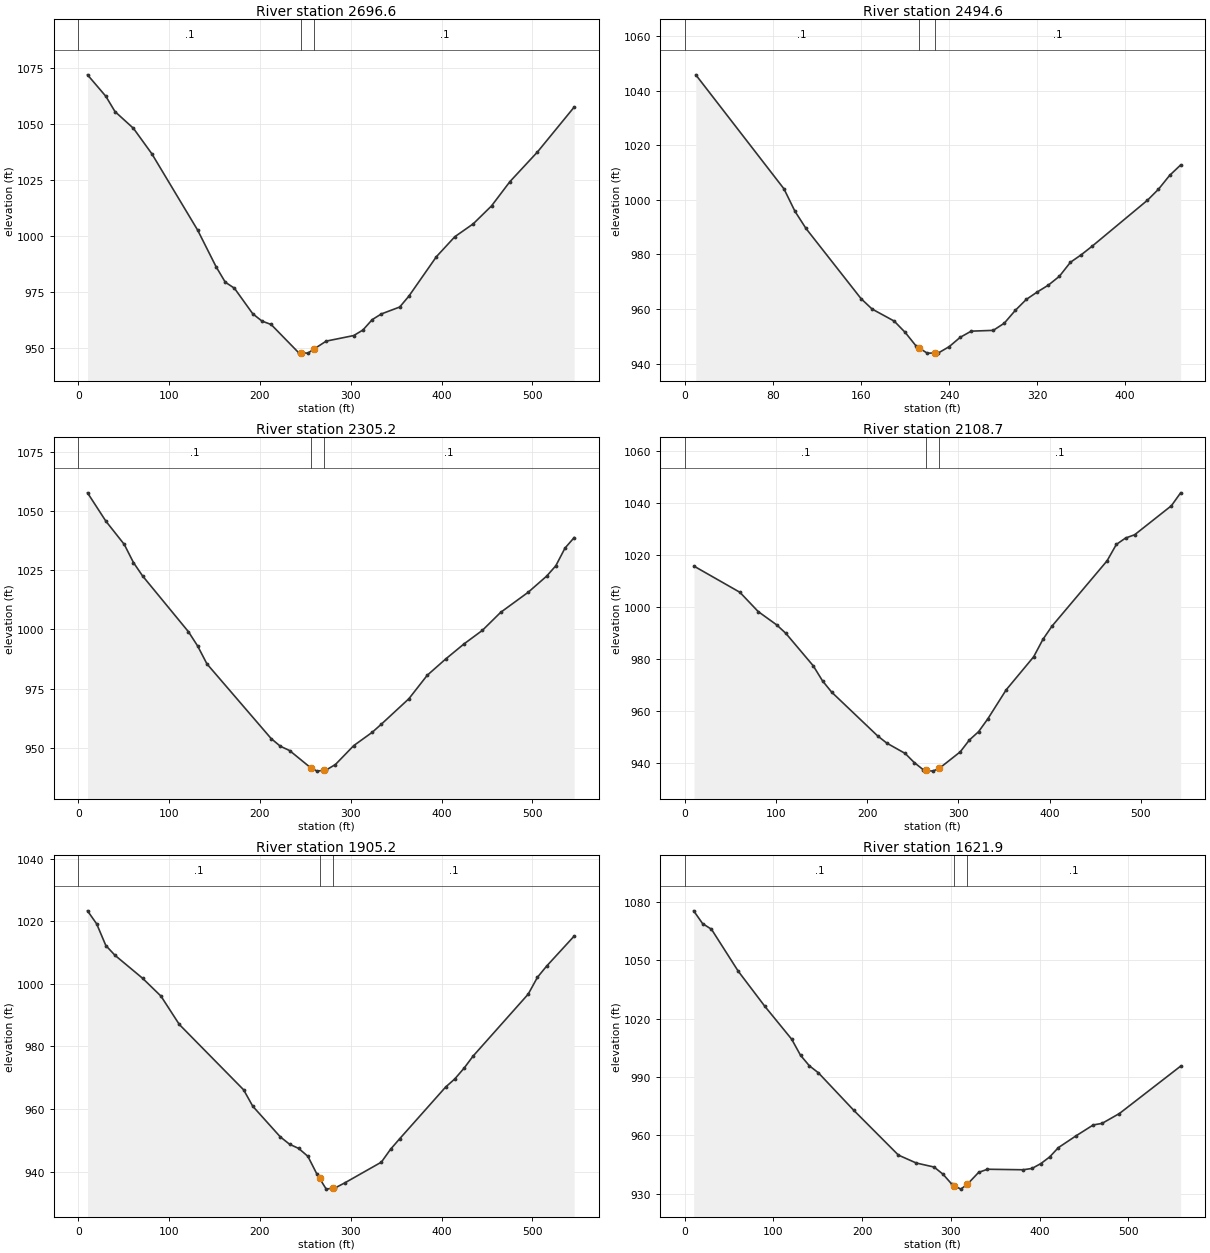
Type RM Length L Ch R = 1 ,2696.6  ,195.7,202,208.2
XS GIS Cut Line= 3
      1701638.85      188397.127     1701459.618      188603.052
     1701280.387      188808.977
#Sta/Elev= 30
    10.1 1072.07    30.3 1062.46    40.4 1055.61    60.7 1048.12    80.9 1036.76
   131.4 1002.56   151.7  986.17   161.8  979.27   171.9  976.55   192.1  965.11
   202.2  961.86   212.3  960.33   242.7  947.67   245.6  947.62   252.8  947.51
   259.9  949.45     273  952.89   303.3  955.38   313.4  957.86   323.6   962.5
   333.7  965.05   353.9  968.15     364  973.02   394.3  990.67   414.6  999.62
   434.8 1005.36     455  1013.4   475.2 1024.24   505.6 1037.55     546 1057.62
#Mann= 3 , 0 , 0
       0      .1       0   245.6    .045       0   259.9      .1       0
Bank Sta=245.6,259.9
XS Rating Curve= 0 ,0
Exp/Cntr=0.3,0.1

Type RM Length L Ch R = 1 ,2494.6  ,185.2,189.5,193.8
XS GIS Cut Line= 2
     1701535.789      188321.476     1701150.367      188554.446
#Sta/Elev= 30
      10 1045.78    90.1    1004   100.1  995.77   110.1  989.49   160.1  963.79
   170.1  959.99   190.2  955.57   200.2  951.42   210.2  946.39     213  945.68
   220.2  943.83   227.4  943.85   230.2  943.86   240.2  946.21   250.2  949.63
   260.2  951.88   280.2  952.17   290.2  954.79   300.2  959.48   310.2   963.5
   320.3  966.26   330.3  968.75   340.3  971.99   350.3  977.11   360.3  979.91
   370.3  983.09   420.3  999.85   430.3 1003.88   440.4 1008.93   450.4 1012.75
#Mann= 3 , 0 , 0
       0      .1       0     213    .045       0   227.4      .1       0
Bank Sta=213,227.4
XS Rating Curve= 0 ,0
Exp/Cntr=0.3,0.1

Type RM Length L Ch R = 1 ,2305.2  ,196.5,196.5,196.5
XS GIS Cut Line= 3
     1701497.655      188191.163     1701239.302      188279.381
     1700980.948        188367.6
#Sta/Elev= 30
    10.1 1057.57    30.3 1045.64    50.6  1035.8    60.7 1028.16    70.8 1022.49
   121.3  998.95   131.4  992.95   141.6  985.42   212.3  953.92   222.4  950.68
   232.6  948.86   255.7  941.64   262.9  940.17   270.1  940.53     273  940.67
   283.1  942.96   303.3  950.94   323.6  956.54   333.7  959.98     364  970.71
   384.2   980.6   404.4  987.43   424.7  993.83   444.9  999.54   465.1 1007.16
   495.4 1015.63   515.7 1022.43   525.8  1026.8   535.9 1034.25     546 1038.69
#Mann= 3 , 0 , 0
       0      .1       0   255.7    .045       0   270.1      .1       0
Bank Sta=255.7,270.1
XS Rating Curve= 0 ,0
Exp/Cntr=0.3,0.1

Type RM Length L Ch R = 1 ,2108.7  ,204,203.5,203.1
XS GIS Cut Line= 2
     1701417.693      188011.206      1700903.44      188187.276
#Sta/Elev= 30
    10.1 1015.68    60.4 1005.63    80.5  998.21   100.7  993.11   110.7  989.88
   140.9  977.33     151  971.57   161.1  967.21   211.4  950.42   221.5  947.64
   241.6  943.67   251.6  940.16   261.7  937.34   264.5  937.21   271.8  936.87
     279  937.93     302  944.29     312  948.84   322.1  952.04   332.2  956.96
   352.3   968.1   382.5  980.84   392.6  987.51   402.6  992.63     463 1017.75
   473.1 1024.02   483.2 1026.48   493.2 1027.75   533.5 1038.91   543.6 1043.87
#Mann= 3 , 0 , 0
       0      .1       0   264.5    .045       0     279      .1       0
Bank Sta=264.5,279
XS Rating Curve= 0 ,0
Exp/Cntr=0.3,0.1

Type RM Length L Ch R = 1 ,1905.2  ,297.5,283.3,269
XS GIS Cut Line= 3
     1701355.392      187811.195     1701099.277      187905.715
     1700843.162      188000.234
#Sta/Elev= 30
    10.1 1023.29    20.2 1019.12    30.3  1012.2    40.4 1009.08    70.8 1001.74
      91  996.05   111.2     987     182  966.13   192.1  960.88   222.4   951.1
   232.6  948.75   242.7   947.4   252.8  944.88   262.9  939.11   265.7  937.81
     273  934.41   280.3  934.73   283.1  934.85   293.2  936.37   333.7  943.03
   343.8  947.14   353.9  950.51   404.4  966.99   414.6  969.62   424.7  973.02
   434.8  976.93   495.4  996.69   505.6 1002.08   515.7 1005.64     546 1015.22
#Mann= 3 , 0 , 0
       0      .1       0   265.7    .045       0   280.3      .1       0
Bank Sta=265.7,280.3
XS Rating Curve= 0 ,0
Exp/Cntr=0.3,0.1

Type RM Length L Ch R = 1 ,1621.9  ,146,140.9,135.8
XS GIS Cut Line= 3
     1701066.269      187429.137     1700870.968      187779.998
     1700849.492      187936.025
#Sta/Elev= 30
      10 1075.34    20.1 1068.76    30.1 1065.86    60.2 1044.35    90.3 1026.25
   120.5 1009.38   130.5  1001.1   140.5  995.68   150.6  992.12   190.7  972.75
   240.9   949.8     261  945.74   281.1  943.67   291.1  940.01   301.2  934.81
   303.9  934.14   311.2  932.32   318.5  934.77   331.3  940.91   341.3  942.54
   381.5  942.27   391.5  942.95   401.6  945.48   411.4  948.85   421.2  953.63
   440.9  959.63   460.6  965.31   470.5   966.1   490.1  971.18   559.1  995.52
#Mann= 3 , 0 , 0
       0      .1       0   303.9    .045       0   318.5      .1       0
Bank Sta=303.9,318.5
XS Rating Curve= 0 ,0
Exp/Cntr=0.3,0.1

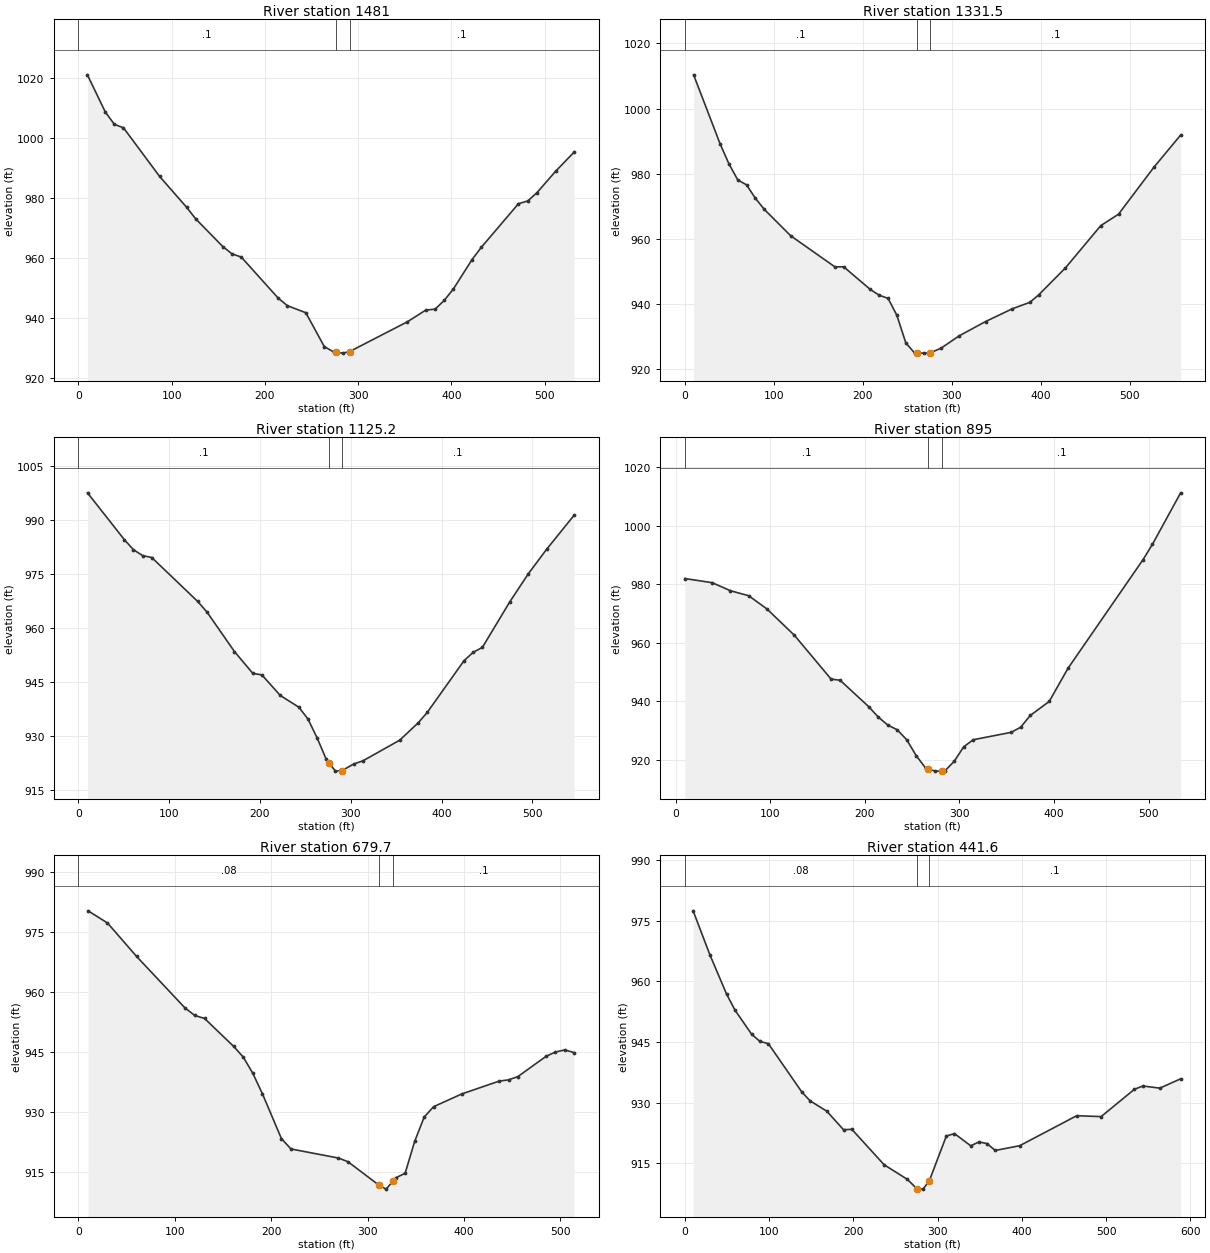
Type RM Length L Ch R = 1 ,1481    ,155.3,149.5,143.8
XS GIS Cut Line= 4
     1700929.654      187409.247     1700820.863      187519.469
     1700756.447      187768.544      1700769.33      187887.355
#Sta/Elev= 30
     9.7 1021.09      29 1008.64    38.7 1004.55    48.4 1003.42    87.1   987.2
   116.2  976.85   125.8  973.04   154.9  963.78   164.8  961.34   174.7  960.28
   214.2   946.6   224.1  944.07   243.9   941.7   263.7  930.41   273.6  928.65
   276.2  928.54   283.5  928.22   290.8  928.73   352.8  938.68   372.6   942.6
   382.5  942.89   392.3  945.82   402.2  949.67   422.1  959.43   432.1  963.55
   471.9  978.09   481.9     979   491.8  981.79   511.7   988.9   531.6  995.32
#Mann= 3 , 0 , 0
       0      .1       0   276.2    .045       0   290.8      .1       0
Bank Sta=276.2,290.8
XS Rating Curve= 0 ,0
Exp/Cntr=0.3,0.1

Type RM Length L Ch R = 1 ,1331.5  ,215.1,206.3,197.5
XS GIS Cut Line= 3
     1700706.972      187361.858     1700639.693      187516.456
     1700652.825      187904.685
#Sta/Elev= 30
     9.9 1010.34    39.7  989.13    49.6  983.01    59.5  978.08    69.4  976.57
    79.3  972.45    89.3  969.05     119  960.94   168.6  951.41   178.6   951.4
   208.4  944.47   218.4  942.69   228.4  941.73   238.3  936.51   248.3  928.09
   258.2  924.95   260.9  924.94   268.2  924.92   275.5  924.96   288.1  926.47
     308  930.18   337.9  934.61   367.8  938.51   387.7  940.51   397.7  942.82
   427.6  951.06   467.4  964.06   487.3  967.56   527.2  982.02   557.1  991.85
#Mann= 3 , 0 , 0
       0      .1       0   260.9    .045       0   275.5      .1       0
Bank Sta=260.9,275.5
XS Rating Curve= 0 ,0
Exp/Cntr=0.3,0.1

Type RM Length L Ch R = 1 ,1125.2  ,222.2,230.2,238.1
XS GIS Cut Line= 3
     1700318.461      187426.426     1700442.532      187669.604
     1700566.603      187912.781
#Sta/Elev= 30
    10.1  997.64    50.6  984.62    60.7   981.8    70.8  980.16    80.9  979.62
   131.4   967.4   141.6  964.46   171.9  953.44   192.1  947.37   202.2  946.92
   222.4   941.2   242.7  937.96   252.8  934.68   262.9  929.41     273  923.43
   275.8  922.51   283.1  920.13   290.5   920.3   303.3  922.12   313.4     923
   353.9  928.75   374.1  933.54   384.2  936.47   424.7  950.88   434.8  953.23
   444.9  954.58   475.2  967.31   495.4  975.05   515.7  981.93     546  991.41
#Mann= 3 , 0 , 0
       0      .1       0   275.8    .045       0   290.5      .1       0
Bank Sta=275.8,290.5
XS Rating Curve= 0 ,0
Exp/Cntr=0.3,0.1

Type RM Length L Ch R = 1 ,895     ,207,215.3,223.7
XS GIS Cut Line= 4
     1700264.649      187515.025     1700237.452      187686.801
     1700253.198      187897.226     1700361.989       187998.86
#Sta/Elev= 30
     9.7     982    38.6  980.59      58  977.83    77.3  976.11    96.6  971.57
   125.6  962.57   164.3   947.6   173.9  947.19   204.1  938.16   214.1  934.64
   224.2  931.88   234.2  930.26   244.3  926.83   254.3  921.39   264.3  917.13
     267  916.86  274.41   916.1   281.8  916.11   284.4  916.12   294.5  919.47
   304.5  924.42   314.6  926.84   354.8  929.38   364.8  931.15   374.9  935.16
   394.9  939.95   414.7  951.26   494.1  988.48     504  993.71   533.8 1011.33
#Mann= 3 , 0 , 0
     9.7      .1       0     267    .045       0   281.8      .1       0
Bank Sta=267,281.8
XS Rating Curve= 0 ,0
Exp/Cntr=0.3,0.1

Type RM Length L Ch R = 1 ,679.7   ,228.7,238.1,247.6
XS GIS Cut Line= 4
     1700110.604      187450.642     1700082.854      187619.522
     1700017.006      187805.612     1700072.833       187940.17
#Sta/Elev= 30
    10.1  980.26    30.2  977.23    60.4  968.86   110.7  955.96   120.8  954.09
   130.9  953.35   161.1  946.36   171.1  943.67     181  939.62   190.9  934.52
   210.6  923.32   220.5  920.72   269.8  918.45   279.7  917.52   311.8  911.66
   319.2  910.68   326.6  912.78   329.1  913.49   338.9  914.65   348.8  922.62
   358.7  928.71   368.5   931.3   397.7  934.48   436.5  937.69   446.2     938
   455.9  938.83   485.1  943.89   494.8  944.96   504.5  945.48   514.2  944.81
#Mann= 3 , 0 , 0
       0     .08       0   311.8    .045       0   326.6      .1       0
Bank Sta=311.8,326.6
XS Rating Curve= 0 ,0
Exp/Cntr=0.3,0.1

Type RM Length L Ch R = 1 ,441.6   ,223,185.9,134.4
XS GIS Cut Line= 6
     1699875.856      187359.006      1699891.96      187576.409
     1699825.129       187640.02     1699966.894      187785.484
     1700008.563      187813.565     1700017.169      187836.664
#Sta/Elev= 30
     9.9  977.42    29.7  966.58    49.5  956.87    59.5  952.88    79.3  946.91
    89.2  945.13    99.1  944.59   138.7  932.67   148.6  930.45   168.5  927.88
   188.3   923.3   198.2   923.4   236.5  914.64   264.1  911.02   275.1  908.76
   282.6  908.61     290  910.61   310.3  921.73   319.9  922.35   339.3  919.32
     349  920.28   358.6  919.87   368.3  918.17   397.3  919.34     465  926.76
     494  926.54   533.5   933.3   543.5  934.11   563.6  933.58   588.3  935.88
#Mann= 3 , 0 , 0
       0     .08       0   275.1    .045       0     290      .1       0
Bank Sta=275.1,290
XS Rating Curve= 0 ,0
Exp/Cntr=0.3,0.1

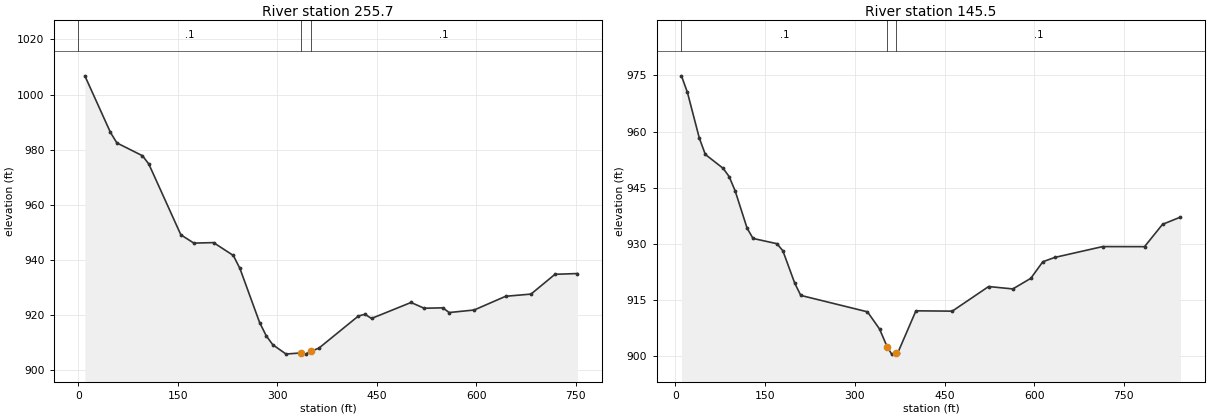
Type RM Length L Ch R = 1 ,255.7   ,106.2,110.2,128.5
XS GIS Cut Line= 6
     1699619.059      187241.616     1699591.862      187403.371
     1699838.073      187662.466     1699906.783      187726.882
     1699965.474      187789.866     1700005.555      187821.358
#Sta/Elev= 30
     9.6  1006.8    48.2  986.26    57.9  982.44    96.5  977.79   106.1  974.77
   154.4  949.08     174  946.07   203.7  946.25   233.5  941.59   243.5  936.86
   273.2  917.24   283.2  912.41   293.1  909.16     313   905.8   335.3  906.18
   342.7  905.76   350.2  906.76   362.6  907.93   422.2   919.6   432.1  920.23
     442  918.71   501.6  924.51   521.4  922.42   549.7  922.57   559.1  920.86
   596.8  921.78   644.3  926.76   682.6  927.56   718.7  934.74   752.7  935.02
#Mann= 3 , 0 , 0
       0      .1       0   335.3    .045       0   350.2      .1       0
Bank Sta=335.3,350.2
XS Rating Curve= 0 ,0
Exp/Cntr=0.3,0.1

Type RM Length L Ch R = 1 ,145.5   ,159.9,145.5,131.1
XS GIS Cut Line= 4
     1699505.974      187248.773     1699490.228      187457.766
     1699753.617      187695.389     1699995.534      187837.104
#Sta/Elev= 30
      10  974.89      20  970.45    39.9  958.23    49.9  953.88    79.8  950.15
    89.8  947.95    99.8  944.14   119.8  934.16   129.7  931.42   169.7  930.01
   179.6  928.13   199.6  919.41   209.6  916.19   321.1   911.8   341.3  907.22
   354.1  902.45   361.6  900.49   369.1  900.73   371.8  900.81   402.2  912.07
     463  911.98   523.8  918.56   564.3  917.92   594.4  920.76   614.4  925.18
   634.4  926.34   714.5  929.24   784.6  929.22   814.7  935.19   844.7  937.12
#Mann= 3 , 0 , 0
      10      .1       0   354.1    .045       0   369.1      .1       0
#XS Ineff= 2 , 0
       0     347             382       0
Permanent Ineff=
       F       F
Bank Sta=354.1,369.1
XS Rating Curve= 0 ,0
Exp/Cntr=0.3,0.1
Stream Node=smsfrk          ,Main            , 0 , 0 ,Upstream end
Stream Node=smsfrk          ,Main            , 0 , 1 ,Downstream end

Chan Stop Cuts=-1
Use User Specified Reach Order=0